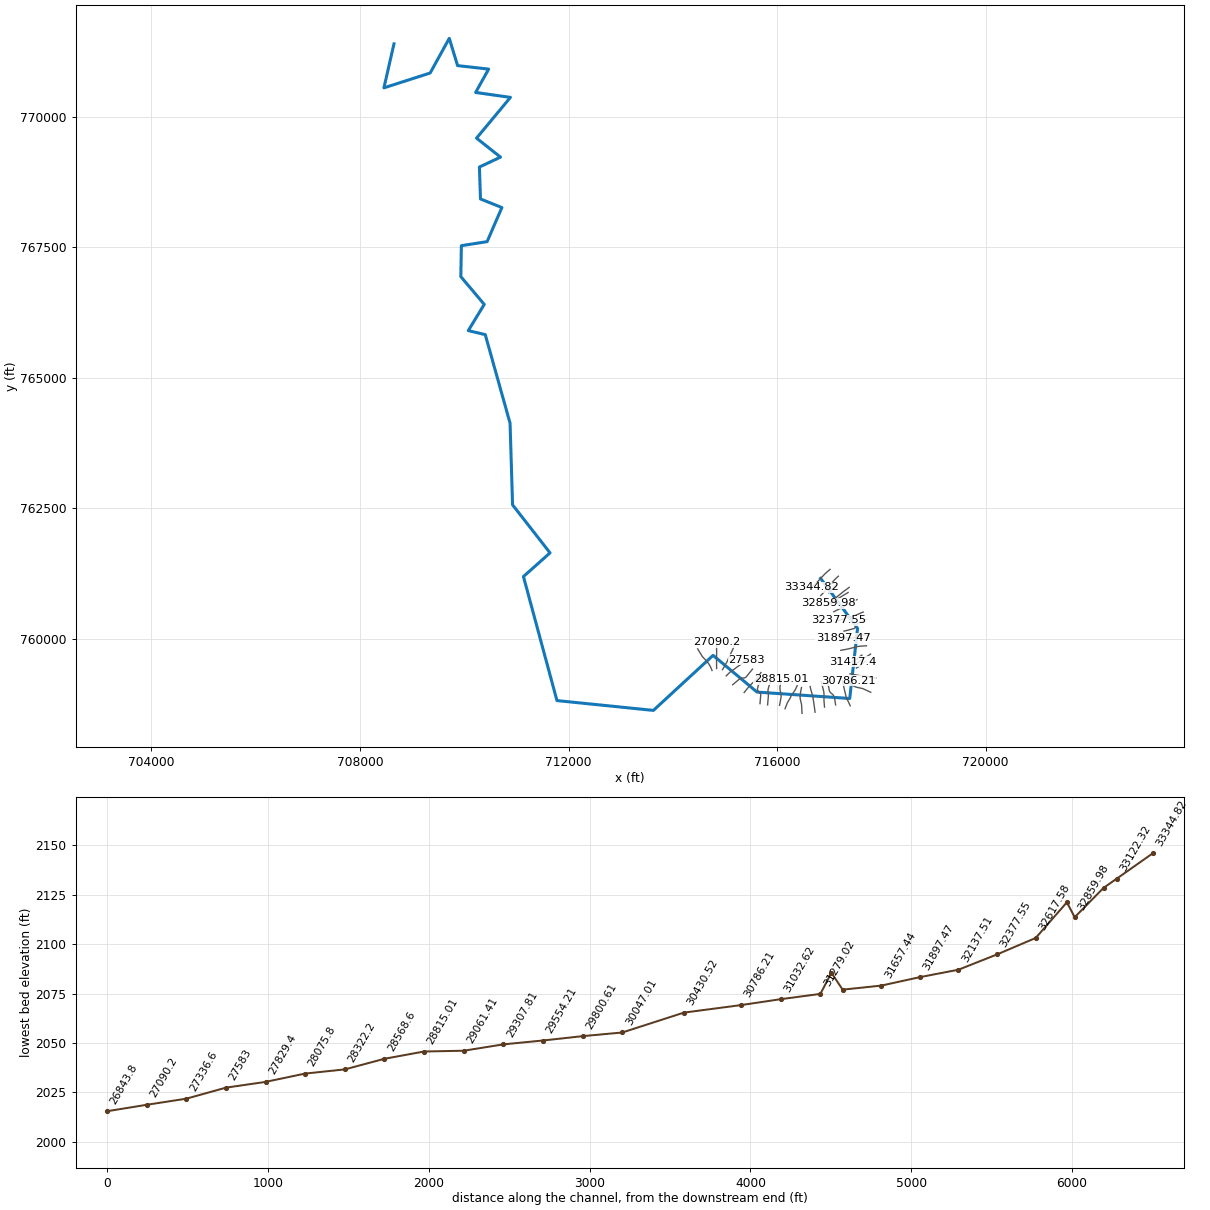
--- 14510_ras.prj (project) ---

Proj Title=14510
Current Plan=p01
Default Exp/Contr=0.3,0.1
English Units
Geom File=g01
Flow File=f01
Plan File=p01
Y Axis Title=Elevation
X Axis Title(PF)=Main Channel Distance
X Axis Title(XS)=Station
BEGIN DESCRIPTION:
RFD model 14510 exported to HEC-RAS
END DESCRIPTION:

--- 14510_ras.p01 (plan) ---

Plan Title=Plan 01
Program Version=4.10
Short Identifier=Plan 01
Geom File=g01
Flow File=f01
Subcritical Flow
Calc Critical at every XS
Secant Critical Depth

--- 14510_ras.f01 (steady flow) ---

Flow Title=Flow 01
Program Version=4.10
Number of Profiles= 6
Profile Names=10yr,25yr,50yr,100yr,100plus,500yr
River Rch & RM=14510,99,33344.82
  148.51  245.86  339.33   428.4  625.47 1147.15
River Rch & RM=14510,99,32377.55
  150.67  249.44  344.28  434.65  634.59 1161.48
River Rch & RM=14510,99,32137.51
  159.25  263.67  363.95  459.48  670.84 1218.13
River Rch & RM=14510,99,31897.47
  165.27  273.64  377.75   476.9  696.27 1257.64
River Rch & RM=14510,99,31657.44
  173.69   287.6  397.05  501.27  731.86  1312.6
River Rch & RM=14510,99, 31417.4
  176.82   292.8  404.24  510.35  745.12 1332.97
River Rch & RM=14510,99,31347.39
  179.59   297.4  410.61   518.4  756.86 1350.98
River Rch & RM=14510,99,31032.62
  186.18  308.31  425.69  537.43  784.65 1393.39
River Rch & RM=14510,99,30786.21
  210.71  348.84  481.61  607.85  887.47  1547.6
River Rch & RM=14510,99,30430.52
     238  393.93  543.85  686.27 1001.96 1716.49
River Rch & RM=14510,99,30047.01
  256.54   424.7  586.45  740.07  1080.5 1831.49
River Rch & RM=14510,99,29800.61
  260.46  431.19  595.41  751.35 1096.98 1855.34
River Rch & RM=14510,99,29554.21
  265.35  439.26  606.56  765.42 1117.51 1884.98
River Rch & RM=14510,99,29307.81
  274.27  454.09   627.1  791.36 1155.39 1939.83
River Rch & RM=14510,99,29061.41
  416.65   690.2  953.86 1203.73 1757.45 2779.61
River Rch & RM=14510,99,28815.01
  428.06  709.28  980.41 1237.39 1806.59 2846.94
River Rch & RM=14510,99, 28568.6
  433.25  717.92   992.4 1252.56 1828.74 2877.04
River Rch & RM=14510,99, 28322.2
  449.59  745.14  1030.2 1300.37 1898.55 2971.54
River Rch & RM=14510,99, 28075.8
  451.87  748.94 1035.48 1307.05  1908.3 2984.71
River Rch & RM=14510,99, 27829.4
  456.96  757.43 1047.28 1322.01 1930.14 3014.26
River Rch & RM=14510,99,   27583
  459.99  762.53 1054.39 1331.05 1943.33 3032.26
River Rch & RM=14510,99, 27336.6
  519.35  862.23 1193.56 1507.96 2201.62 3380.89
River Rch & RM=14510,99, 27090.2
  602.35 1002.54 1390.25 1758.91    2568 3870.09
River Rch & RM=14510,99, 26843.8
  606.69 1009.88 1400.53 1772.01 2587.14 3895.31
River Rch & RM=14510,99,26583.27
  635.33 1058.04 1467.84 1857.63 2712.14 4058.41
River Rch & RM=14510,99,26350.99
  644.89 1074.21 1490.51 1886.55 2754.36 4113.66
River Rch & RM=14510,99,26104.59
  649.97 1082.77 1502.49  1901.8 2776.63 4142.62
River Rch & RM=14510,99,25858.19
  653.55 1088.79  1510.9  1912.5 2792.25 4162.84
River Rch & RM=14510,99,25611.79
  732.65 1221.34  1695.7 2147.04 3134.68 4599.97
River Rch & RM=14510,99,25365.39
  751.35 1252.77 1739.63  2202.9 3216.24 4703.59
River Rch & RM=14510,99,25118.99
  765.07 1276.04 1772.31 2244.67 3277.21 4781.75
River Rch & RM=14510,99,24872.59
  774.74  1292.4 1795.27 2273.97 3319.99  4836.3
River Rch & RM=14510,99,24626.19
  782.45 1305.45 1813.58 2297.34 3354.12 4879.76
River Rch & RM=14510,99,24379.78
  784.38 1308.71 1818.16 2303.18 3362.64  4890.6
River Rch & RM=14510,99,24133.38
  820.76  1370.3  1904.6 2413.53 3523.75 5094.86
River Rch & RM=14510,99,23886.98
  843.39  1408.8  1958.8 2482.92 3625.06 5223.54
River Rch & RM=14510,99,23640.58
   855.5 1429.37 1987.76 2519.98 3679.17 5292.01
River Rch & RM=14510,99,23394.18
  858.25 1434.07 1994.39 2528.47 3691.57 5307.76
River Rch & RM=14510,99,23147.78
  862.82 1441.88 2005.41 2542.61 3712.22 5333.97
River Rch & RM=14510,99,22916.82
  873.57 1460.22 2031.28 2575.79 3760.65 5395.37
River Rch & RM=14510,99,22679.03
  876.54 1465.28 2038.42 2584.95 3774.03 5412.31
River Rch & RM=14510,99,22408.57
  935.04 1565.41 2179.97 2766.77 4039.49 5748.05
River Rch & RM=14510,99,22171.75
  940.38 1574.55 2192.89 2783.37 4063.72 5778.54
River Rch & RM=14510,99,21934.92
  947.72  1587.1 2210.63 2806.16    4097 5820.35
River Rch & RM=14510,99,21698.09
  949.05 1589.38 2213.85  2810.3 4103.04 5827.94
River Rch & RM=14510,99,21461.26
  953.04 1596.22 2223.51 2822.71 4121.16 5850.68
River Rch & RM=14510,99,21224.43
  978.28  1639.5 2284.79 2901.51 4236.21 5995.19
River Rch & RM=14510,99,20987.61
  980.71 1643.65 2290.65 2909.05 4247.21 6008.94
River Rch & RM=14510,99,20750.78
  992.11  1663.2  2318.3 2944.58 4299.08 6073.77
River Rch & RM=14510,99,20513.95
    1054 1769.69 2469.38 3139.25 4583.31 6429.31
River Rch & RM=14510,99,20244.78
 1055.93 1773.01 2474.07 3145.29 4592.13 6440.26
River Rch & RM=14510,99,19803.47
 1058.93 1778.16 2481.37 3154.69 4605.84 6457.27
River Rch & RM=14510,99,19566.64
 1066.21 1790.65 2499.07 3177.47  4639.1 6498.52
River Rch & RM=14510,99,19329.81
 1067.49 1792.85  2502.2 3181.49 4644.97 6505.79
River Rch & RM=14510,99,19092.98
 1224.54  2060.7  2880.1 3665.95 5352.29 7364.55
River Rch & RM=14510,99,18856.15
  1246.1 2097.74 2932.59 3733.51 5450.93 7484.13
River Rch & RM=14510,99,18619.33
 1312.27 2211.72 3094.44 3942.18 5755.58 7853.13
River Rch & RM=14510,99,18471.52
 1318.98 2223.27 3110.82 3963.28 5786.39 7890.21
River Rch & RM=14510,99, 18233.8
 1321.82 2228.16 3117.77 3972.23 5799.45 7905.92
River Rch & RM=14510,99,17947.41
 1329.72 2241.75 3137.06 3997.09 5835.76 7949.63
River Rch & RM=14510,99,17520.64
 1347.66 2272.65 3180.95 4053.68 5918.38 8049.01
River Rch & RM=14510,99,17282.92
 1349.87 2276.47 3186.37 4060.67 5928.58 8061.26
River Rch & RM=14510,99, 17045.2
 1365.18 2302.83 3223.78 4108.89 5998.98  8145.7
River Rch & RM=14510,99,16807.48
  1373.4 2316.99  3243.9 4134.83 6036.85  8191.1
River Rch & RM=14510,99,16479.66
 1456.91 2461.03 3448.63 4398.96 6422.48 8651.83
River Rch & RM=14510,99, 15856.6
 1488.61 2515.68  3526.3 4499.15 6568.77 8825.48
River Rch & RM=14510,99,15358.93
 1493.12 2523.47 3537.36 4513.43 6589.61 8850.18
River Rch & RM=14510,99,14861.26
 1519.54 2569.04 3602.14    4597 6711.63  8994.6
River Rch & RM=14510,99,14363.59
 1615.22 2734.16 3836.96 4900.07  7154.1 9515.55
River Rch & RM=14510,99,13865.92
 1624.59 2750.36 3860.03 4929.86 7197.59  9566.6
River Rch & RM=14510,99,13368.25
 1632.23 2763.57 3878.83 4954.15 7233.05  9608.2
River Rch & RM=14510,99,12870.59
 1641.78 2780.08 3902.32 4984.49 7277.35  9660.1
River Rch & RM=14510,99,12372.92
 1650.14 2794.53 3922.91  5011.1  7316.2 9705.69
River Rch & RM=14510,99,11875.25
 1732.52 2937.05 4125.91 5273.44 7699.2210152.94
River Rch & RM=14510,99,11377.58
 1740.33  2950.6 4145.25 5298.47 7735.7710195.61
River Rch & RM=14510,99,10879.91
 1746.65 2961.56 4160.88 5318.71 7765.32 10230.1
River Rch & RM=14510,99,10336.63
 1786.62 3030.93  4259.9 5446.91 7952.4910448.18
River Rch & RM=14510,99,9766.505
 1797.47 3049.78 4286.82 5481.78 8003.3910507.44
River Rch & RM=14510,99,8863.705
 1856.32  3151.8 4432.34 5670.05 8278.2710825.59
River Rch & RM=14510,99,8391.573
 1867.13 3170.55  4459.1 5704.69 8328.8510884.03
River Rch & RM=14510,99,7893.904
 1873.16 3181.01 4474.04 5724.04 8357.0910916.66
River Rch & RM=14510,99,7166.945
 1880.28 3193.37 4491.68 5746.88 8390.4510955.18
River Rch & RM=14510,99,  6400.9
  1887.3  3205.6 4509.18 5769.59  8423.610993.64
River Rch & RM=14510,99,5654.646
 1893.02 3215.59 4523.49 5788.17 8450.7211025.17
River Rch & RM=14510,99,4907.895
 1936.62 3291.29 4631.57 5928.13 8655.0611260.45
River Rch & RM=14510,99,4410.227
 1941.98 3300.63 4644.93 5945.47 8680.3911289.73
River Rch & RM=14510,99,3912.558
 1942.33 3301.25 4645.82 5946.63 8682.0711291.68
River Rch & RM=14510,99,3420.693
 1940.19 3297.52 4640.48 5939.69 8671.9511279.97
River Rch & RM=14510,99,2560.342
 1942.33 3301.25 4645.82 5946.63 8682.0711291.68
Boundary for River Rch & Prof#=14510,99,1
Up Type= 0
Dn Type= 2
Boundary for River Rch & Prof#=14510,99,2
Up Type= 0
Dn Type= 2
Boundary for River Rch & Prof#=14510,99,2
Up Type= 0
Dn Type= 2
Boundary for River Rch & Prof#=14510,99,2
Up Type= 0
Dn Type= 2
Boundary for River Rch & Prof#=14510,99,2
Up Type= 0
Dn Type= 2
Boundary for River Rch & Prof#=14510,99,2
Up Type= 0
Dn Type= 2

--- 14510_ras.g01 (geometry) ---

Geom Title=14510
Program Version=4.10

River Reach=14510,99
Reach XY= 30
716833.253919899761153.271626964717542.452515781760194.084038273
717392.035849124758849.500704914715613.980293542758972.556260481
714771.785849065759676.584038287713626.178210229758621.097927153
711777.011543542758809.431260467711134.164321363761188.250704899
711644.025432438761642.417371571710925.761543542 762562.90348272
710877.464443862764129.901375204710402.011543542765828.042371586
710076.594876885765905.125704914710382.428210229766407.625704914
709933.261543483766940.125704914709943.678210258767533.875704929
710437.428210229767611.375704914710720.645802855768264.986816034
710310.645802885768429.431260467710289.673580587769042.209038273
710694.673580617769232.209038273710234.634007633769596.236175433
710884.673580617770378.042371586710216.948547304 770472.29279159
710467.119511873 770920.28751494709871.462793916770987.049900845
709711.740430683771510.487291902709345.420936465 770845.55672802
708458.268244177770560.834428489 708651.30870977771405.020106822

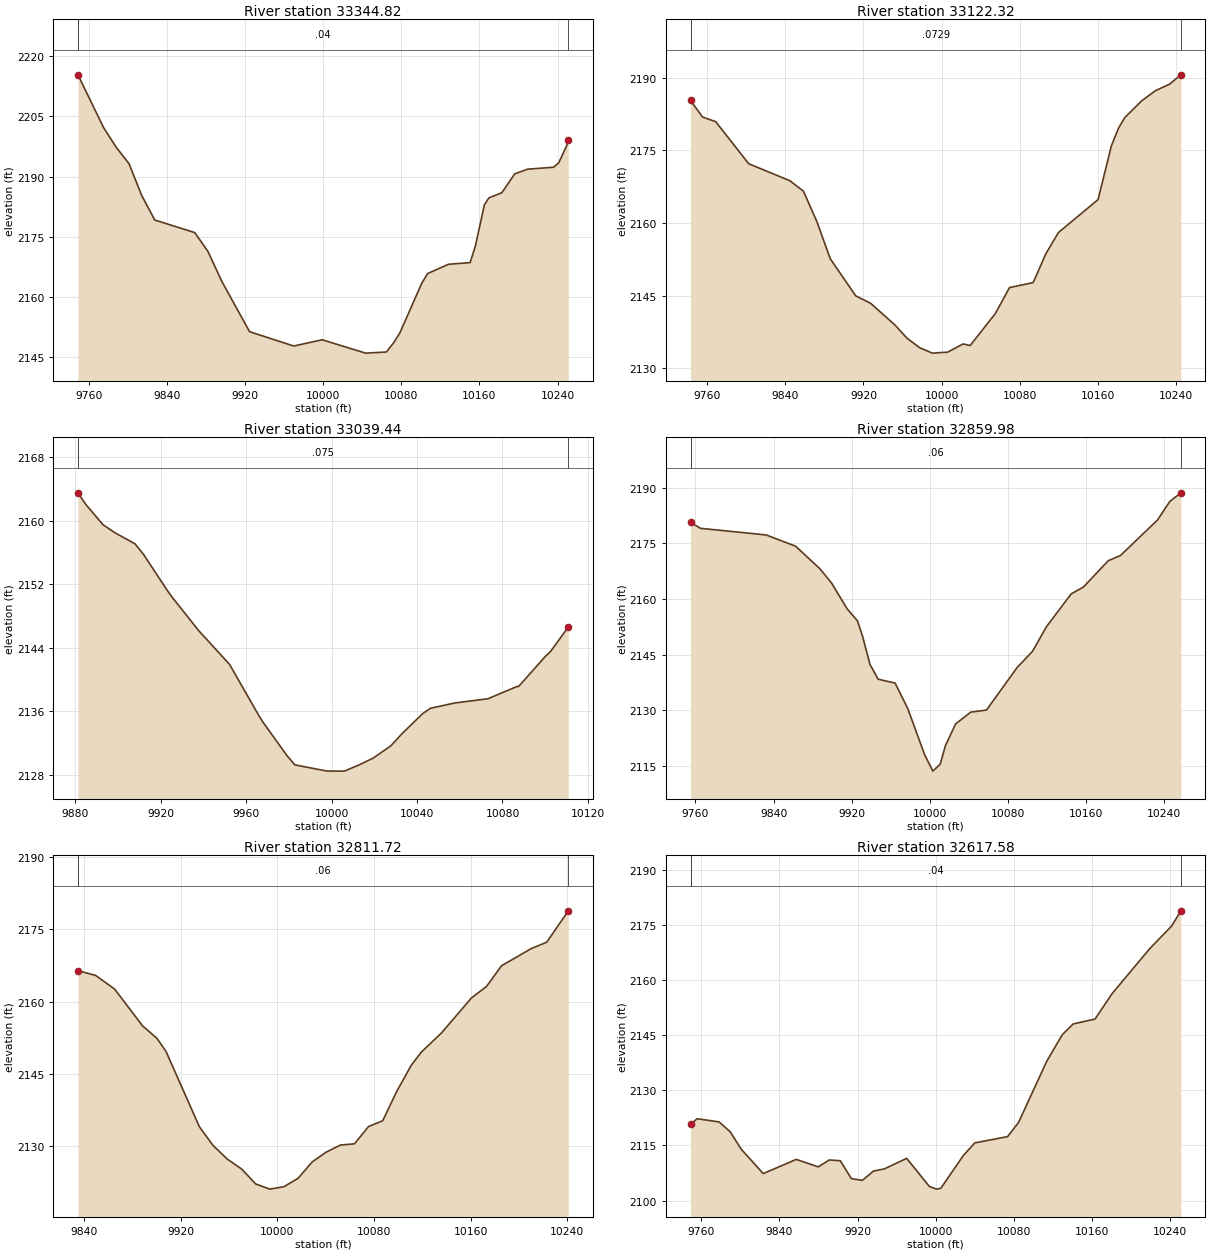
Type RM Length L Ch R = 1 ,33344.82,222.506900,222.506900,222.506900
XS GIS Cut Line= 6
717015.250014569761325.712703156716966.162664736761284.995977032
716914.078352647761237.358327633716768.074755917761082.120898407
716714.560019572761031.411337865716653.574210876760978.554999751
#Sta/Elev= 30
9749.0242215.4049775.334  2202.29788.3262197.2629801.3182193.2049814.3762185.236
9827.611 2179.149868.5832175.9929882.135 2171.289896.2862163.8159924.7082151.236
9969.9592147.653    99992149.21710043.442145.88110064.722146.15810072.212148.475
10078.632150.97110100.792163.25110106.912165.75710128.34 2168.0810150.522168.497
10155.892172.67110165.062182.91510169.672184.66210182.932185.95410196.16 2190.68
10209.392191.83310235.862192.32110241.142193.41310249.092197.59510250.982199.134
#Mann= 3 , 0 , 0
9749.024    0.04       09749.024    0.04       010250.98    0.04       0
#XS Ineff= 2 , 0
       0                               0
Bank Sta=9749.024,10250.98
Exp/Cntr=0.3,0.1

Type RM Length L Ch R = 1 ,33122.32,82.877200,82.877200,82.877200
XS GIS Cut Line= 6
717174.041974744761195.270977199717126.942800795761152.071195855
717077.827490447761101.572079937717040.891974884761059.099098537
716921.775300317760912.995532608 716836.62322715 760824.55533752
#Sta/Elev= 30
9742.9592185.2679755.2282181.8619768.7982180.8789802.5362172.2189844.6332168.713
9858.5832166.5529872.5322160.1659886.0242152.6119912.1012144.9649927.3412143.428
9951.7982139.0379964.705 2136.219977.612 2134.269990.5192133.15410006.192133.357
10022.022135.05210029.222134.72310055.02 2141.3310069.512146.67310093.722147.704
10106.622153.62510119.522158.01610160.132164.81910173.72 2175.8910181.132179.586
10187.572181.75910204.882185.20810218.992187.29810233.092188.60310244.912190.552
#Mann= 3 , 0 , 0
9742.959  0.0729       09742.959  0.0729       010244.91  0.0729       0
#XS Ineff= 2 , 0
       0                               0
Bank Sta=9742.959,10244.91
Exp/Cntr=0.3,0.1

Type RM Length L Ch R = 1 ,33039.44,179.460000,179.460000,179.460000
XS GIS Cut Line= 2
717142.834915221761047.807799727716989.474882662760876.992153719
#Sta/Elev= 29
9881.2662163.5049885.0392162.0159892.9942159.4879898.4782158.4919907.9622157.084
9911.917 2155.779922.9312151.2719925.3562150.3569937.899 2146.119952.2342141.892
9965.6732135.5659967.8372134.6279979.1122130.3999982.8052129.2269997.774 2128.45
10005.992128.43810012.742129.20610019.432130.07410027.712131.61910032.87 2133.13
10042.682135.69510046.31 2136.3610057.652137.02310073.182137.55610086.622139.083
10087.592139.11410100.062142.89410102.552143.52310110.822146.602
#Mann= 3 , 0 , 0
9881.266   0.075       09881.266   0.075       010110.82   0.075       0
#XS Ineff= 2 , 0
       0                               0
Bank Sta=9881.266,10110.82
Exp/Cntr=0.3,0.1

Type RM Length L Ch R = 1 ,32859.98,48.257000,48.257000,48.257000
XS GIS Cut Line= 6
717381.527088887760981.035815272717270.619097249 760899.08888169
717183.510012616760828.562657903717181.968089113760827.288895009
717092.517814178760754.024471719716986.040270255760672.068230786
#Sta/Elev= 30
9754.9522180.6649765.1092179.023 9832.422177.2299862.5362174.2029887.4032168.128
9899.3482164.277 9915.242157.3489925.814 2154.099931.1322149.877 9938.682142.341
9947.024 2138.379964.4142137.315 9977.28 2130.49  9994.72117.97210003.012113.596
10010.542115.47310015.94  2120.510026.322126.31610041.79 2129.4910057.892130.043
10089.452141.56810105.232145.94610119.352152.53710144.662161.35910157.28 2163.23
10182.522170.28110195.142171.709   102332181.26110245.612186.26210256.922188.582
#Mann= 3 , 0 , 0
9754.952    0.06       09754.952    0.06       010256.92    0.06       0
#XS Ineff= 2 , 0
       0                               0
Bank Sta=9754.952,10256.92
Exp/Cntr=0.3,0.1

Type RM Length L Ch R = 1 ,32811.72,194.141800,194.141800,194.141800
XS GIS Cut Line= 3
717361.030083448760882.602886617717129.119790316760742.957978964
717020.645620972760662.537474081
#Sta/Elev= 30
9835.1042166.4229849.8432165.4189865.4892162.5929888.6142154.9649900.5082152.389
9907.9992149.6719935.5272134.101 9946.772130.2349958.8732127.3349970.5462125.316
9982.2192122.2099993.8922121.14710005.572121.65110017.242123.39310028.91 2126.78
10040.582128.82210052.262130.27810063.93 2130.54 10075.62134.13110087.282135.312
10098.952141.42910110.942146.82810119.182149.52310135.972153.52110160.742160.772
10173.182163.13910185.632167.44310210.532171.03310222.982172.30710240.852178.812
#Mann= 3 , 0 , 0
9835.104    0.06       09835.104    0.06       010240.85    0.06       0
#XS Ineff= 2 , 0
       0                               0
Bank Sta=9835.104,10240.85
Exp/Cntr=0.3,0.1

Type RM Length L Ch R = 1 ,32617.58,240.036400,240.036400,240.036400
XS GIS Cut Line= 6
717531.005096197760746.199807943717341.942075812760647.708005171
717310.349334616760628.825396008717308.675002216 760627.73149884
717273.685668446 760607.32305127 717086.44415554760513.416163874
#Sta/Elev= 30
9749.0152120.7229755.7862122.2689778.3372121.3959789.6132118.7169800.8882113.994
9823.4392107.3379857.2662111.1959879.8172109.1669891.0932111.0469902.3692110.832
9913.6442105.964 9924.922105.4829936.1952108.0059947.4712108.6219970.2822111.471
9993.5822103.811   100012103.10210005.252103.33610028.412112.28910039.982115.688
 10073.62117.40310084.782121.23710113.612137.88110129.532145.13610140.72 2148.07
10163.092149.40510180.53 2156.3110219.032168.56310241.412174.70810250.98 2178.87
#Mann= 3 , 0 , 0
9749.015    0.04       09749.015    0.04       010250.98    0.04       0
#XS Ineff= 2 , 0
       09963.544                       0
Bank Sta=9749.015,10250.98
Exp/Cntr=0.3,0.1

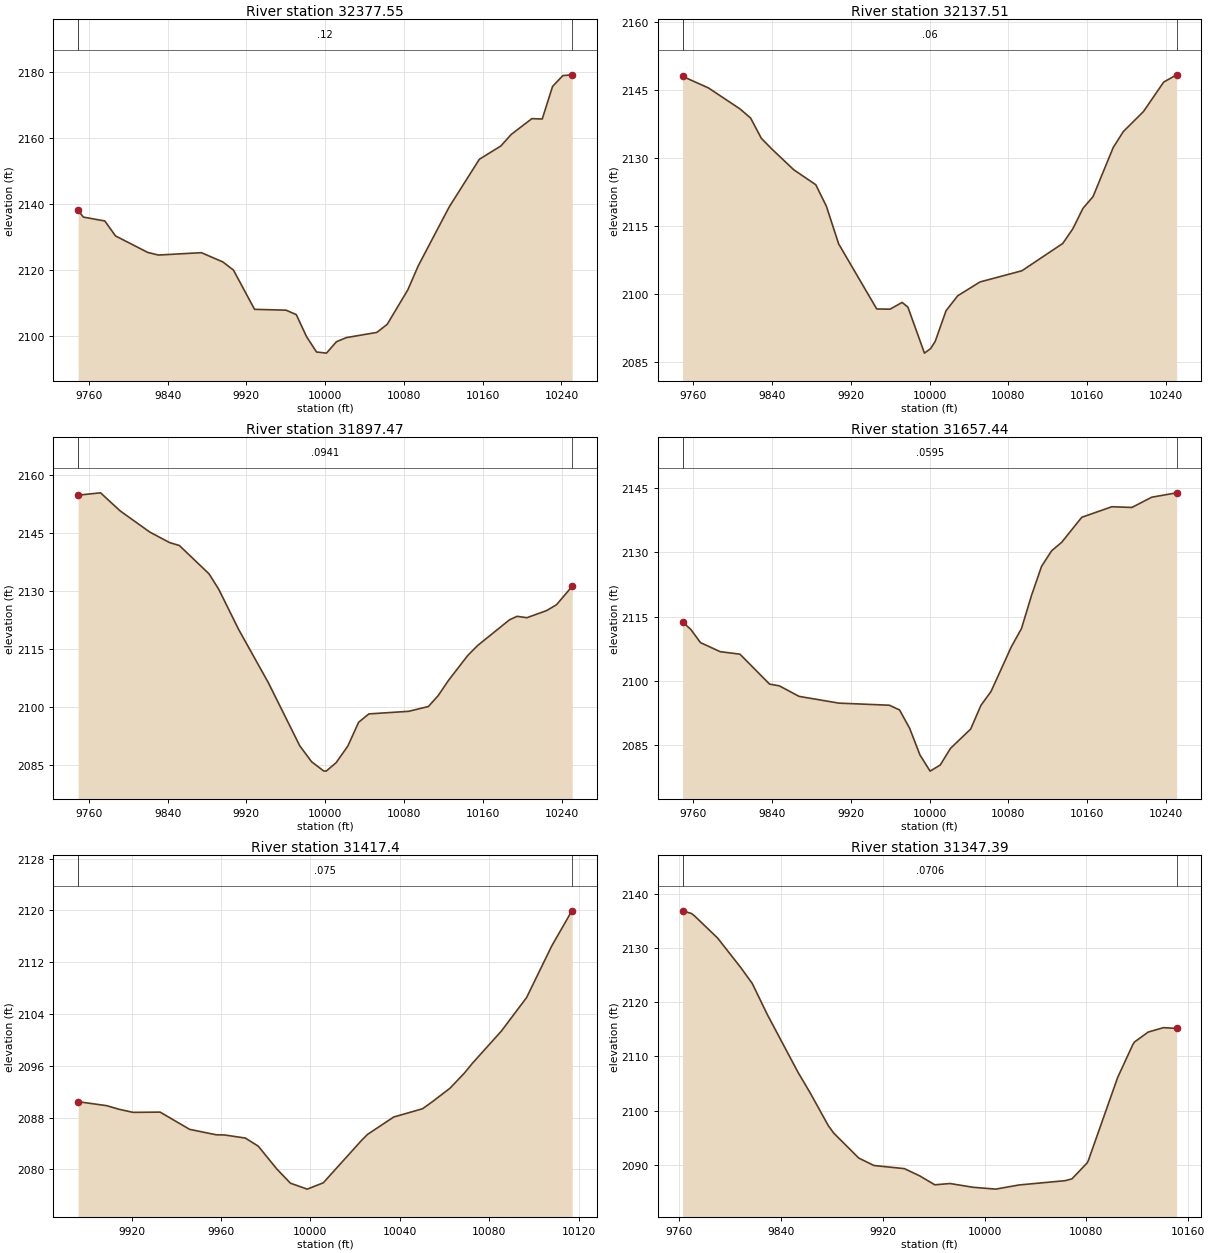
Type RM Length L Ch R = 1 ,32377.55,240.036500,240.036500,240.036500
XS GIS Cut Line= 6
 717649.88083561760507.705595535 717511.12463624760447.586374139
717460.115168874760427.841395534717434.282931046760420.452592621
717367.408519535760407.454598963717175.990881838760346.288637239
#Sta/Elev= 30
9749.0342138.0229754.3542135.979 9776.152134.7989787.0482130.2739819.743 2125.28
9830.6422124.4839874.2352125.2039896.0312122.4029906.8222119.9419928.2682108.048
9960.2732107.7899970.6742106.4479981.0752099.7879991.2232095.12710001.342094.784
10011.452098.23510021.592099.48510052.552101.06110063.052103.51110084.052113.985
10094.54 2121.2110126.042139.06510156.65 2153.4910178.532157.51610189.03 2161.01
10210.022165.79210220.522165.67810231.022175.54310241.522178.83410250.982179.056
#Mann= 3 , 0 , 0
9749.034    0.12       09749.034    0.12       010250.98    0.12       0
#XS Ineff= 2 , 0
       0                               0
Bank Sta=9749.034,10250.98
Exp/Cntr=0.3,0.1

Type RM Length L Ch R = 1 ,32137.51,240.036500,240.036500,240.036500
XS GIS Cut Line= 6
717709.645640067760362.282056046717552.813255971760290.608446485
717522.700728218 760262.29347376717495.619902245760208.510553956
717476.167726568760191.454604603717282.143564185760140.514758882
#Sta/Elev= 30
9749.1062148.0779775.3492145.528 9807.422140.9019818.2692138.8699829.1172134.409
9839.9652132.0149861.9442127.4939884.3712124.1849895.1572119.4459907.5972111.146
9946.2922096.7829959.8132096.7419972.0842098.2339977.9562097.1849994.7482087.048
   10001 2088.0510005.662089.64610016.682096.40310028.532099.69710051.172102.744
 10093.72105.20910135.182111.23110145.43 2114.4710155.682118.96510165.922121.562
10186.412132.38410196.662135.89810217.152140.32210237.652146.81410250.822148.412
#Mann= 3 , 0 , 0
9749.106    0.06       09749.106    0.06       010250.82    0.06       0
#XS Ineff= 2 , 0
       0                               0
Bank Sta=9749.106,10250.82
Exp/Cntr=0.3,0.1

Type RM Length L Ch R = 1 ,31897.47,240.036400,240.036400,240.036400
XS GIS Cut Line= 6
717757.755323488760072.586322844717565.720109363 760061.75245659
717533.221355903760050.125717899 717490.09417979760020.307181354
717464.922800139760013.139900582717269.053207836760007.195247902
#Sta/Elev= 30
9749.1062154.7559771.8812155.3559791.8982150.6579821.9242145.1919841.9422142.478
 9851.952141.7079881.9772134.3959891.9852130.3539912.0482120.0099942.2812106.191
9974.2072089.8419986.2052085.7219998.4292083.337   100012083.286 10011.12085.466
10022.992089.77510033.962095.93810044.352098.10210084.842098.77610104.842100.019
10114.842102.86410124.84 2106.6510144.842113.25510154.84 2115.82 10187.12122.452
10194.852123.37510204.872123.01810224.892124.864 10234.92126.37110250.872131.165
#Mann= 3 , 0 , 0
9749.106  0.0941       09749.106  0.0941       010250.87  0.0941       0
#XS Ineff= 2 , 0
       0                               0
Bank Sta=9749.106,10250.87
Exp/Cntr=0.3,0.1

Type RM Length L Ch R = 1 ,31657.44,240.036500,240.036500,240.036500
XS GIS Cut Line= 6
717713.165772939759860.757962191717592.726426585759852.371469689
717542.495529357759845.983105199717376.170069101759803.287298306
717291.464074848759785.906529249717220.167626483759773.470786624
#Sta/Elev= 30
9749.0562113.7419757.2422112.0919767.2662108.9659787.3142106.8489807.3632106.268
9837.4362099.294 9847.462098.8759867.5082096.4259907.818 2094.869959.1792094.369
9969.5152093.2679979.8512088.9449990.1872082.79710000.522079.00910010.842080.441
10021.152084.28910041.782088.82610052.092094.30510062.412097.56610083.04 2107.98
10093.342112.23110103.552119.95910113.752126.73310123.96 2130.3610134.172132.333
10154.592138.16710185.172140.63110205.48 2140.4610225.782142.85810250.992143.871
#Mann= 3 , 0 , 0
9749.056  0.0595       09749.056  0.0595       010250.99  0.0595       0
#XS Ineff= 2 , 0
       0                               0
Bank Sta=9749.056,10250.99
Exp/Cntr=0.3,0.1

Type RM Length L Ch R = 1 , 31417.4,70.006600,70.006600,70.006600
XS GIS Cut Line= 6
717626.264948306759681.606154844717610.274081005759672.890224132
717585.000954658759655.723066837717527.093242066759603.253838003
717489.781461137759576.676439075717446.844503731759554.603135797
#Sta/Elev= 27
9896.0662090.4659908.8952089.8449914.2782089.2989920.6532088.8159932.7422088.852
9945.9612086.1889957.8372085.351  9961.62085.3229970.8832084.8459976.6792083.588
9984.9312080.0789991.0642077.8729998.5792076.95810005.762077.93610023.022084.545
10025.592085.42110037.242088.09410050.142089.37210054.482090.43910062.422092.539
10068.832094.86110072.492096.40410085.452101.38110096.692106.53710107.942114.509
10116.242119.50310117.112119.939
#Mann= 3 , 0 , 0
9896.066   0.075       09896.066   0.075       010117.11   0.075       0
#XS Ineff= 2 , 0
       0                               0
Bank Sta=9896.066,10117.11
Exp/Cntr=0.3,0.1

Type RM Length L Ch R = 1 ,31347.39,68.375500,68.375500,68.375500
XS GIS Cut Line= 3
717790.848297417759700.132172599717616.558339924759585.942200452
717466.308376521759486.777224615
#Sta/Elev= 30
9762.5562136.8529769.5482136.3619771.9212135.9329790.1682131.8199808.4162126.356
9817.3692123.4429829.3242117.6599853.2342107.1059863.1582103.1569877.1442097.219
9881.4052095.8489901.0542091.244 9913.012089.869 9936.922089.2939948.875 2087.97
 9960.83 2086.319972.7892086.5469990.7872085.85610008.732085.51210027.09 2086.28
 10063.42087.07310068.642087.40810080.62 2090.3510081.562090.80210104.592106.113
10116.572112.20910117.862112.66310128.552114.48310140.532115.29710150.95 2115.16
#Mann= 3 , 0 , 0
9762.556  0.0706       09762.556  0.0706       010150.95  0.0706       0
#XS Ineff= 2 , 0
       0                               0
Bank Sta=9762.556,10150.95
Exp/Cntr=0.3,0.1

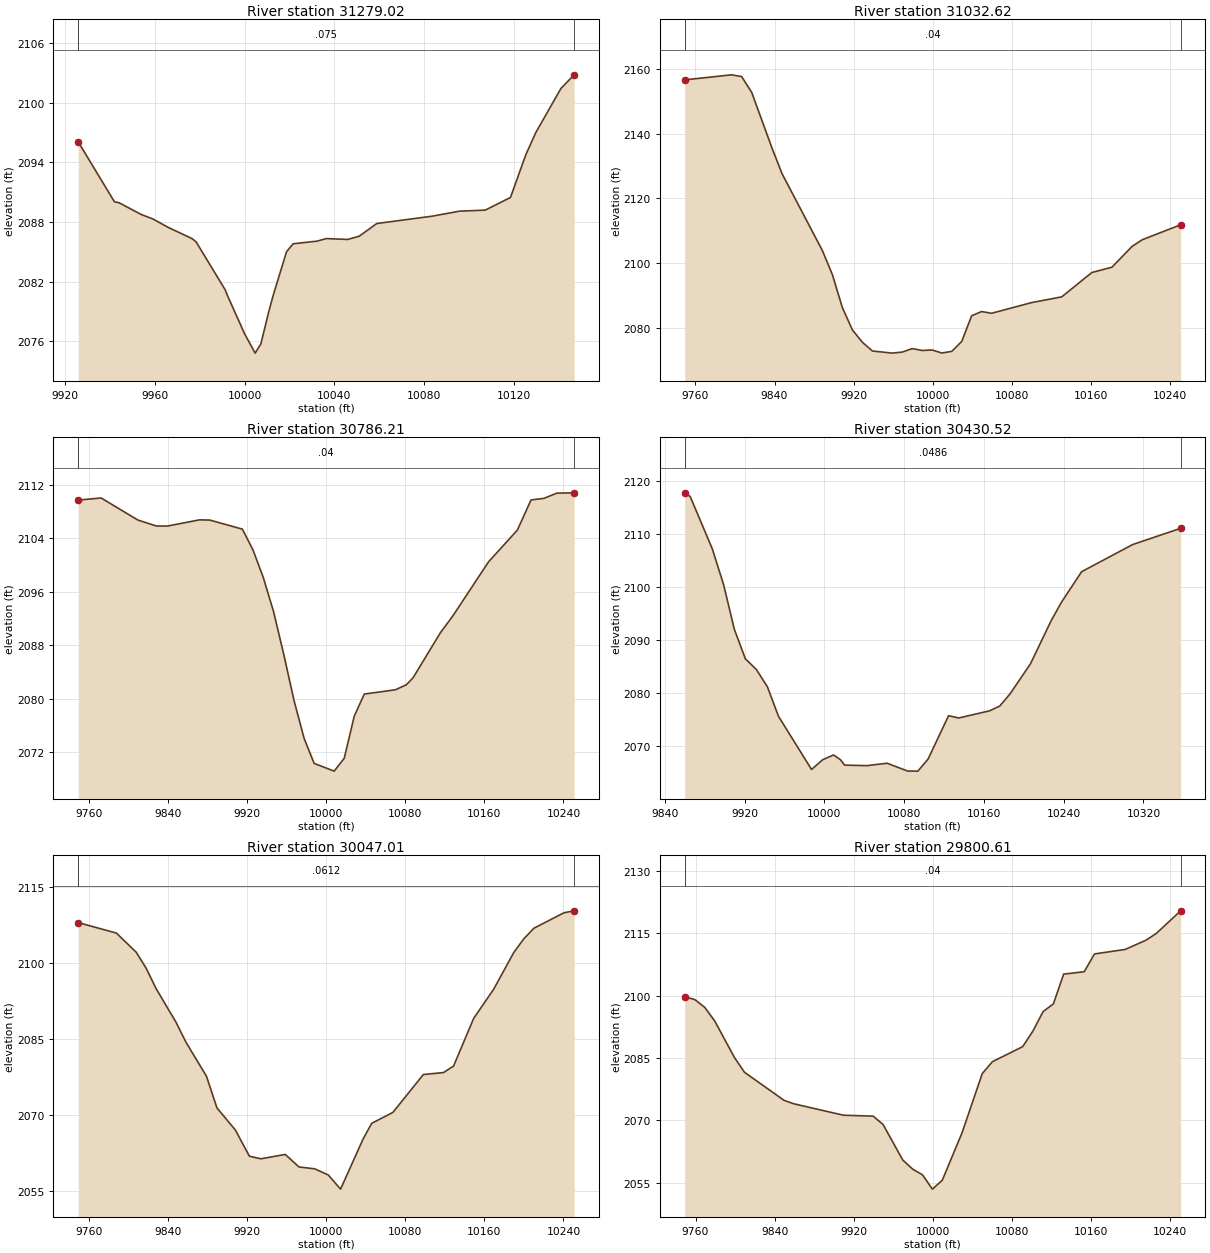
Type RM Length L Ch R = 1 ,31279.02,246.401200,246.401200,246.401200
XS GIS Cut Line= 6
717699.181614971759562.161710403717683.190747667759553.445779683
717657.917621323759536.278622361717600.009908731759483.809393559
717562.698127804759457.231994633717519.761170401759435.158691355
#Sta/Elev= 30
9925.8072096.0719941.9582090.0379944.0192089.941 9953.92 2088.76 9959.052088.316
9966.0092087.4579976.5712086.3339978.3662086.0069991.3722081.166 9992.21 2080.67
10000.022076.73710004.682074.81610007.222075.74610010.692078.94410012.692080.611
10018.652085.01110021.622085.816 10032.32086.08110036.322086.33810045.952086.252
10051.012086.57310058.912087.85510083.472088.58810095.742089.09510107.232089.201
10118.472090.47410125.322094.77810129.712096.98210140.96 2101.4410146.85 2102.81
#Mann= 3 , 0 , 0
9925.807   0.075       09925.807   0.075       010146.85   0.075       0
#XS Ineff= 2 , 0
       0                               0
Bank Sta=9925.807,10146.85
Exp/Cntr=0.3,0.1

Type RM Length L Ch R = 1 ,31032.62,246.401200,246.401200,246.401200
XS GIS Cut Line= 6
717891.351935871759242.712364968717718.040630637759278.006613842
717672.580044829 759283.85770509717627.766453615759283.084728181
717589.668401185759287.020564647717396.913174617759322.647937131
#Sta/Elev= 30
9749.0582156.6089796.4922158.1679806.725 2157.639816.958 2152.699837.425 2135.54
9847.6372127.5879888.3382103.9029898.5132096.4339908.6882086.1929918.8632079.288
 9929.012075.4659939.0922072.8059959.2572072.144 9969.342072.479 9979.362073.541
 9989.362072.9729999.3612073.10610009.37 2072.1910019.392072.69310029.452075.765
 10039.52083.69110049.552084.99610059.652084.46210100.232087.77210130.672089.541
10161.11 2097.0610181.462098.69910201.882105.14310212.082107.18110250.962111.814
#Mann= 3 , 0 , 0
9749.058    0.04       09749.058    0.04       010250.96    0.04       0
#XS Ineff= 2 , 0
       0                               0
Bank Sta=9749.058,10250.96
Exp/Cntr=0.3,0.1

Type RM Length L Ch R = 1 ,30786.21,355.699000,355.699000,355.699000
XS GIS Cut Line= 6
717795.819641872758968.264328887717639.407962264759039.995226965
717518.071735763759066.105815417717478.812524816759081.622030359
717411.443529893759128.718138483 717357.35034859759188.480326593
#Sta/Elev= 30
9749.0712109.7259772.2962110.0429809.4062106.7429828.0712105.8499839.2262105.836
9871.8432106.7689882.2492106.7349915.1772105.379 9925.832102.2979936.2552098.174
9946.6812093.0639957.1062086.5939967.4892079.6979977.633 2074.079987.7772070.315
10008.072069.15810018.222071.07610028.36 2077.3710038.512080.69210070.022081.334
10081.012082.07510087.822083.11610115.672089.90510128.112092.38110164.212100.477
10193.412105.23110207.262109.74810220.292109.98510233.312110.76510250.872110.813
#Mann= 3 , 0 , 0
9749.071    0.04       09749.071    0.04       010250.87    0.04       0
#XS Ineff= 2 , 0
       0                               0
Bank Sta=9749.071,10250.87
Exp/Cntr=0.3,0.1

Type RM Length L Ch R = 1 ,30430.52,383.504600,383.504600,383.504600
XS GIS Cut Line= 3
 717401.70089227 758709.98491402717323.570911318758875.259873733
717252.953428566759181.769798994
#Sta/Elev= 30
9859.9722117.8139865.5192117.1119887.6412107.2719899.0492100.4789909.7632092.092
9920.8252086.5289931.8862084.5049942.9472081.2379954.0082075.6989987.1912065.658
9998.2522067.48310009.312068.39610016.042067.52310020.372066.477 10042.52066.378
10063.042066.83210083.562065.35910093.832065.34510104.092067.62610124.61 2075.79
10134.872075.36510165.662076.70910175.92 2077.6110186.182079.89210206.712085.565
10227.232093.60610237.492097.08610258.022102.93710309.332108.06910357.322111.119
#Mann= 3 , 0 , 0
9859.972  0.0486       09859.972  0.0486       010357.32  0.0486       0
#XS Ineff= 2 , 0
       0                               0
Bank Sta=9859.972,10357.32
Exp/Cntr=0.3,0.1

Type RM Length L Ch R = 1 ,30047.01,246.401100,246.401100,246.401100
XS GIS Cut Line= 6
717121.675150847758726.565231309717097.281852314758877.922066359
717071.226389993758922.012018817 717019.74996192758964.393305681
717001.450049737 758996.79189704716965.287048157759185.145537993
#Sta/Elev= 30
9749.1832108.0369787.7842105.9639807.871 2102.179817.9142099.0129827.9572094.978
9848.0892088.3259858.3032084.323 9878.962077.6159889.5262071.3679908.2292066.971
9922.3232061.8129933.895 2061.29 9958.652062.155 9972.532059.6739988.3082059.312
10002.162058.08710014.592055.289 10037.42065.22510046.082068.31310067.452070.459
10098.33 2077.9710118.752078.359 10128.92079.64810149.212089.07210169.512094.866
10189.812102.11910199.962104.82210210.122106.91610240.572109.97810250.872110.364
#Mann= 3 , 0 , 0
9749.183  0.0612       09749.183  0.0612       010250.87  0.0612       0
#XS Ineff= 2 , 0
       0                               0
Bank Sta=9749.183,10250.87
Exp/Cntr=0.3,0.1

Type RM Length L Ch R = 1 ,29800.61,246.401200,246.401200,246.401200
XS GIS Cut Line= 6
716908.528439805758684.773713044716898.114297994758808.598174036
716898.058898627758944.273638287716895.824315863758970.091736869
716882.684176679759031.004013888716840.760218299759178.874914065
#Sta/Elev= 30
9749.0212099.7469759.2972099.0699769.3462097.1949779.395 2093.929799.4942085.084
9809.5432081.5719849.6552074.8029859.6752073.9689909.707 2071.23 9939.712071.007
9949.7112069.0359969.7142060.4549979.7192058.2559989.7262056.8789999.7342053.439
10009.742055.58410029.822067.04310050.182081.24810060.412084.102 10091.12087.737
 10101.42091.46210111.792096.17910122.192098.03810132.582105.19610153.372105.765
10163.762110.04910194.942111.14110215.73 2113.3410226.132114.94210250.942120.428
#Mann= 3 , 0 , 0
9749.021    0.04       09749.021    0.04       010250.94    0.04       0
#XS Ineff= 2 , 0
       0                               0
Bank Sta=9749.021,10250.94
Exp/Cntr=0.3,0.1

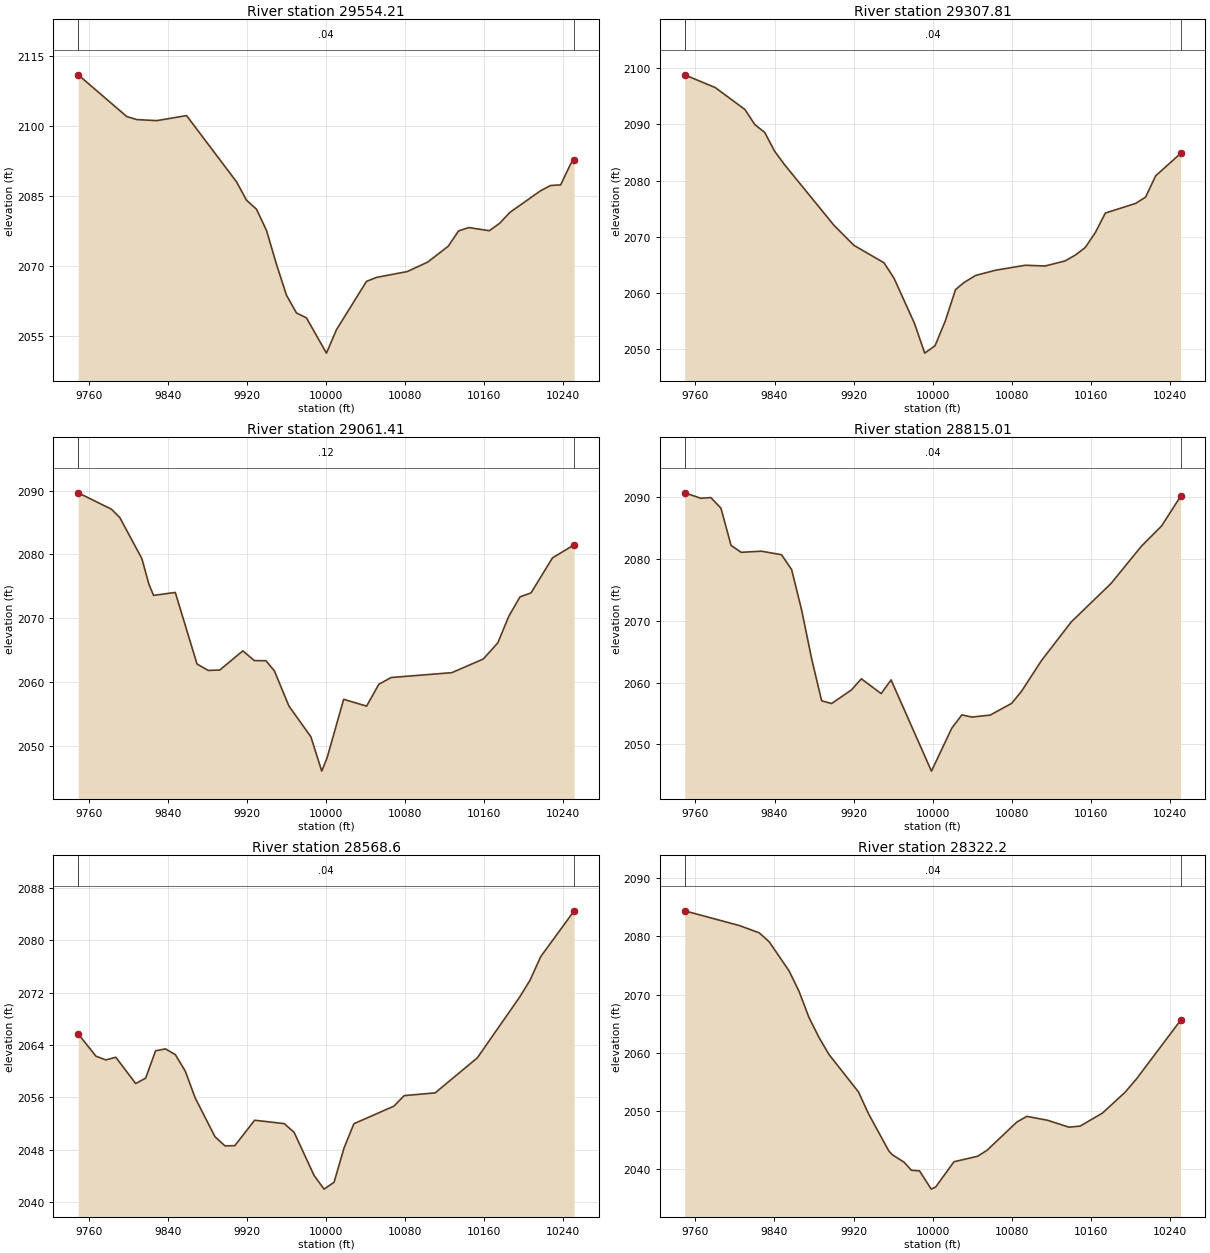
Type RM Length L Ch R = 1 ,29554.21,246.401200,246.401200,246.401200
XS GIS Cut Line= 6
716726.892164994 758586.18801091716713.410335909758692.810731408
716687.164443484758868.847130822 716676.52597062758913.056291176
716647.240711118759016.220731734716632.549308979759078.280646555
#Sta/Elev= 30
9749.0212111.0089798.222 2102.049808.3012101.3969828.4612101.1689858.7072102.251
9909.2682088.025 9919.382084.0799929.4932082.1339939.6052077.5899949.717 2070.29
9959.8292063.6739969.942 2059.869980.0542058.80510000.272051.23610010.372056.258
10040.812066.64810051.09 2067.5110081.972068.74910102.76 2070.7910123.552074.198
10133.952077.47810144.342078.20210165.132077.53110175.532079.11410185.922081.462
10216.762086.07310227.042087.23810237.322087.37210247.592091.94610250.972092.702
#Mann= 3 , 0 , 0
9749.021    0.04       09749.021    0.04       010250.97    0.04       0
#XS Ineff= 2 , 0
       0                               0
Bank Sta=9749.021,10250.97
Exp/Cntr=0.3,0.1

Type RM Length L Ch R = 1 ,29307.81,246.401200,246.401200,246.401200
XS GIS Cut Line= 6
716476.729112493758564.015363953716468.856760557758728.206714642
716442.574043613758843.001927126716438.664854026758877.558331502
 716443.77403171758939.181300673 716466.76280055759059.815678851
#Sta/Elev= 30
 9749.062098.8379780.0552096.5619810.0652092.6619820.0682089.9689830.0712088.582
9840.0752085.2349850.1022082.8449900.246 2072.029920.378 2068.479950.7932065.364
9960.9312062.6119981.5882054.5829991.9742049.28210002.392050.59610012.762054.994
10023.132060.58710031.432061.816 10043.52063.11910063.632064.04310093.66 2064.93
10113.812064.79610134.032065.70410144.21 2066.7210154.392068.08710164.572070.739
10174.752074.22910205.292075.93210215.472077.06110225.652080.84810250.912084.841
#Mann= 3 , 0 , 0
 9749.06    0.04       0 9749.06    0.04       010250.91    0.04       0
#XS Ineff= 2 , 0
       0                               0
Bank Sta=9749.06,10250.91
Exp/Cntr=0.3,0.1

Type RM Length L Ch R = 1 ,29061.41,246.401200,246.401200,246.401200
XS GIS Cut Line= 6
716151.724649113758653.110798016716197.511373964758770.056597443
716244.380752893758847.858687649716272.256402805758907.340011287
716343.105567895759008.307903457716383.844871957759095.241152402
#Sta/Elev= 30
9749.1082089.6539782.7122087.0919791.2032085.778 9813.49 2079.369820.6482075.344
9825.353 2073.599847.3372074.051 9869.322062.8449880.6492061.8369892.3242061.899
9915.672  2064.99927.3472063.3769939.0212063.3559947.5282061.796 9962.372056.241
 9984.542051.4469995.5272046.065   10001 2048.1910017.682057.312 10040.92056.248
 10053.32059.66810065.692060.72510127.192061.48910158.932063.623 10173.62066.137
10184.862070.34410196.122073.35610207.322073.98810228.982079.466 10250.9 2081.51
#Mann= 3 , 0 , 0
9749.108    0.12       09749.108    0.12       0 10250.9    0.12       0
#XS Ineff= 2 , 0
       0                               0
Bank Sta=9749.108,10250.9
Exp/Cntr=0.3,0.1

Type RM Length L Ch R = 1 ,28815.01,246.401200,246.401200,246.401200
XS GIS Cut Line= 6
716046.285092409 758719.06188107716076.036154413 758879.32213359
716074.720682197758925.571532196716056.991855822759006.662426993
716053.097908144 759061.48886396716076.182138436759213.847700054
#Sta/Elev= 30
9749.0762090.681 9765.362089.8079775.578 2089.919785.7952088.1969796.0122082.184
 9806.232081.0579826.6642081.2439847.0992080.6669857.3162078.2649867.4712071.694
9877.557 2063.859887.6432057.0569897.7292056.5999917.8542058.8069927.8572060.601
9947.8992058.2079957.9272060.424  9998.8 2045.6710019.312052.60210029.562054.764
10039.812054.41310058.282054.73510080.032056.63710090.032058.60510110.052063.537
10140.162069.787 10180.62076.03410211.252082.05110231.672085.32210250.932090.116
#Mann= 3 , 0 , 0
9749.076    0.04       09749.076    0.04       010250.93    0.04       0
#XS Ineff= 2 , 0
       0                               0
Bank Sta=9749.076,10250.93
Exp/Cntr=0.3,0.1

Type RM Length L Ch R = 1 , 28568.6,246.401200,246.401200,246.401200
XS GIS Cut Line= 6
715816.877273982758727.169161877715831.893108091 758902.16570314
715824.343531744758996.862408441715825.569449485759022.466016546
715843.596387344759089.743963691715891.237843512759216.764114425
#Sta/Elev= 30
9749.0512065.7199766.9822062.3119777.0372061.7369787.0932062.1459807.2052058.131
 9817.262058.9439827.3162063.1279837.3722063.4269847.4052062.5339857.4252060.019
9867.4462055.9279887.4872049.9939897.5072048.6079907.528 2048.639927.563 2052.52
9957.5672052.0029967.5682050.6649987.7452044.0789997.839 2041.9910007.942043.036
10018.022048.26510028.042051.98710068.542054.673 10078.92056.28110110.292056.703
10152.912062.05310195.632071.30710206.312073.93110216.992077.50210250.912084.524
#Mann= 3 , 0 , 0
9749.051    0.04       09749.051    0.04       010250.91    0.04       0
#XS Ineff= 2 , 0
       0                               0
Bank Sta=9749.051,10250.91
Exp/Cntr=0.3,0.1

Type RM Length L Ch R = 1 , 28322.2,246.401200,246.401200,246.401200
XS GIS Cut Line= 6
715670.918631441758750.573536154715686.832313914758937.060098236
715622.982510536759008.107360079715621.380681303 759030.24982462
715638.464974307 759100.43644818715696.144294559759203.265677641
#Sta/Elev= 30
9749.2712084.4079804.4452081.886 9824.63 2080.639834.6972079.0989854.832 2074.09
9864.8992070.5849874.9222066.1079884.9292062.7119894.9362059.7949924.997 2053.31
9935.0272049.6019955.653 2043.189959.0942042.5349971.1592041.2349978.4862039.858
9986.7432039.7499998.5482036.617 10003.12036.99110021.54 2041.3210045.412042.259
10054.912043.27710085.162048.14210095.272049.10910116.372048.43710137.872047.252
10149.092047.44110171.542049.659 10194.62053.26310206.232055.575 10250.72065.615
#Mann= 3 , 0 , 0
9749.271    0.04       09749.271    0.04       0 10250.7    0.04       0
#XS Ineff= 2 , 0
       0                               0
Bank Sta=9749.271,10250.7
Exp/Cntr=0.3,0.1

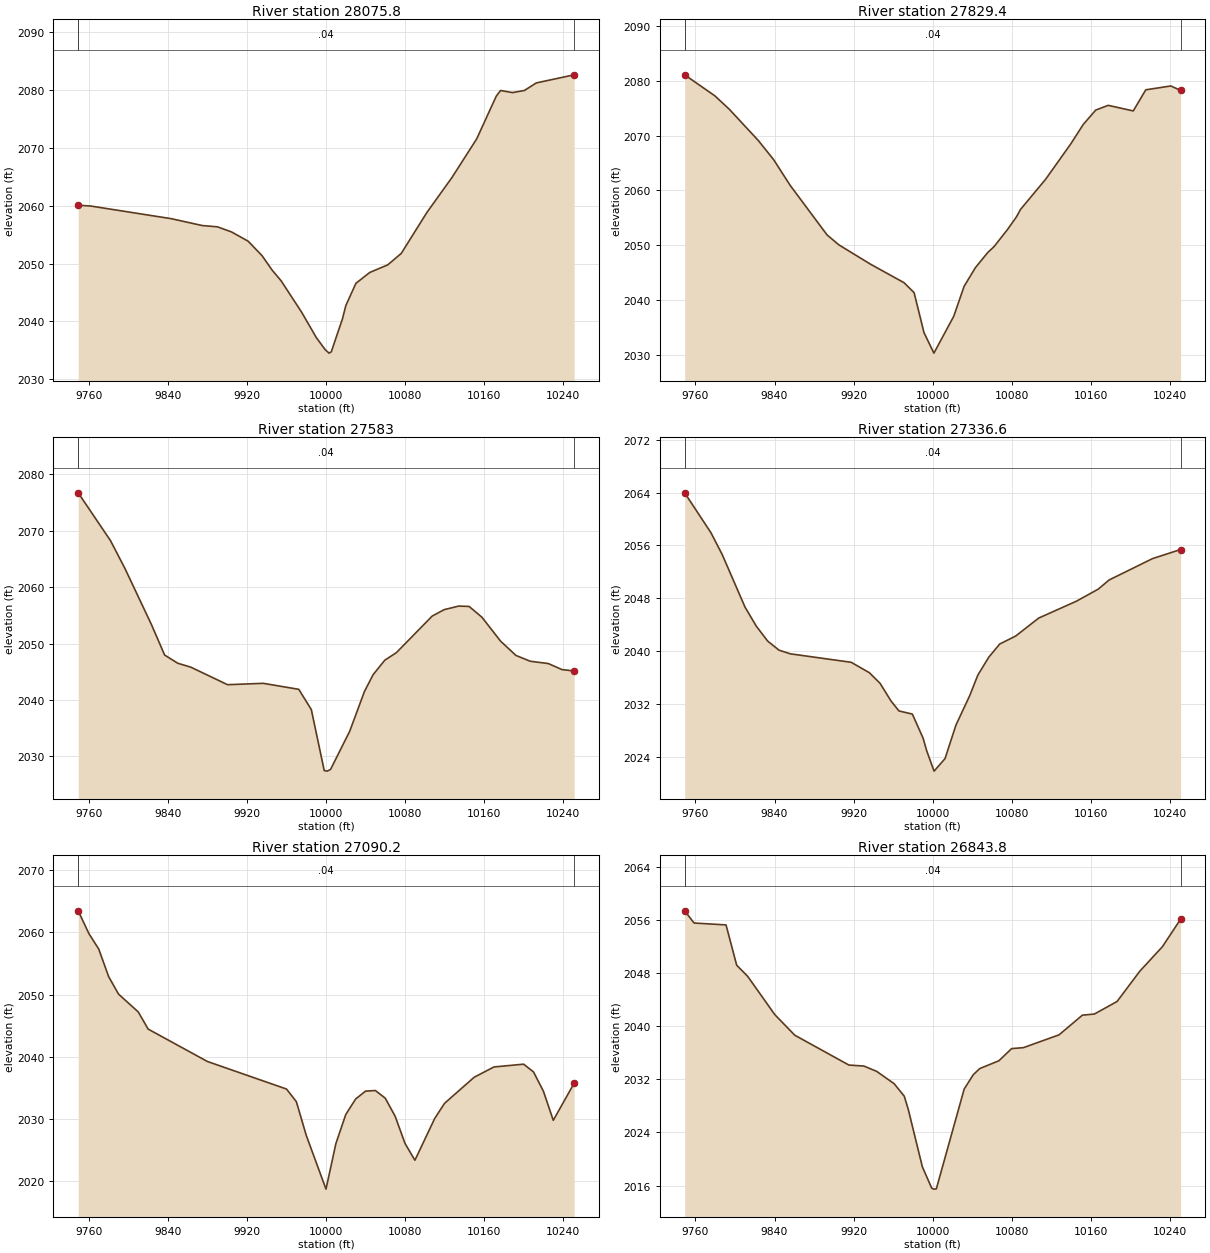
Type RM Length L Ch R = 1 , 28075.8,246.401200,246.401200,246.401200
XS GIS Cut Line= 6
715367.294153916758963.806865623715474.579047502759097.319183182
715560.396282317759176.872404356715593.551655151  759212.2190721
715633.285295423759264.009019538715689.091037545759346.740076337
#Sta/Elev= 30
9749.0352060.0869761.6912059.9469843.523 2057.759874.5182056.5719890.015 2056.35
9904.2322055.4649920.9542053.8759935.116 2051.369945.3272048.8599954.4222047.009
9974.9682041.639 9990.122037.174    99992035.11610002.892034.51310005.14 2034.73
10016.482040.455 10019.92042.74610030.08 2046.5810044.152048.46710062.27 2049.77
10075.982051.75510101.992058.852 10127.22064.85410152.352071.56310172.112078.935
10176.482079.92110188.542079.558 10200.62079.92610212.672081.23410250.952082.631
#Mann= 3 , 0 , 0
9749.035    0.04       09749.035    0.04       010250.95    0.04       0
#XS Ineff= 2 , 0
       0                               0
Bank Sta=9749.035,10250.95
Exp/Cntr=0.3,0.1

Type RM Length L Ch R = 1 , 27829.4,246.401200,246.401200,246.401200
XS GIS Cut Line= 6
 715146.75115459759112.763056657715271.442878448759217.873139802
715316.680740916759238.337237403715375.423763677759244.811520891
715400.708279558759256.802863946 715526.95826518759412.837782035
#Sta/Elev= 30
9749.1092081.1229779.6222077.2889794.1752074.851 9823.592069.1299839.0422065.649
9856.1072060.8689893.2142051.8779905.1122050.0699937.3232046.5189971.0042043.163
9981.2122041.3459991.2632034.03110001.272030.29610021.332037.02210031.822042.496
10043.242045.89910055.762048.67810062.082049.73910075.792052.88410084.872055.205
10088.992056.55810114.322062.05210139.64 2068.4810152.312072.04210164.972074.683
10177.642075.54810202.962074.52810215.632078.38410240.962079.08810250.882078.274
#Mann= 3 , 0 , 0
9749.109    0.04       09749.109    0.04       010250.88    0.04       0
#XS Ineff= 2 , 0
       0                               0
Bank Sta=9749.109,10250.88
Exp/Cntr=0.3,0.1

Type RM Length L Ch R = 1 ,   27583,246.401200,246.401200,246.401200
XS GIS Cut Line= 6
715022.985213123759283.898954181715101.878060982759360.398557044
715198.239245776 759426.73343815715233.213579138759456.025556404
715326.912779403759517.968195358715413.830072207759595.865297631
#Sta/Elev= 30
9749.0862076.7089781.7942068.2269796.4112063.2879823.1682053.3669836.5472047.955
9849.9252046.4979862.9982045.8119900.1992042.7029936.2842042.9469972.2612041.883
9984.9722038.2969998.0292027.492   100012027.38310004.442027.68910023.882034.472
10038.662041.47310047.492044.471 10059.32047.042 10071.12048.38810107.292054.865
10119.542056.01310134.142056.63410144.642056.57310157.642054.65710176.472050.424
10192.042047.88710206.45 2046.8610224.782046.44810238.672045.37610250.932045.139
#Mann= 3 , 0 , 0
9749.086    0.04       09749.086    0.04       010250.93    0.04       0
#XS Ineff= 2 , 0
       0                               0
Bank Sta=9749.086,10250.93
Exp/Cntr=0.3,0.1

Type RM Length L Ch R = 1 , 27336.6,246.401200,246.401200,246.401200
XS GIS Cut Line= 6
 714952.07451137759401.884394386715039.758971502759556.976355382
715066.081898378759618.359218765715069.250890595759624.574743521
715141.927275421759777.136794438715175.324041196 759850.92081994
#Sta/Elev= 30
 9749.072063.9769775.6252057.9399787.1122054.6069810.0872046.6769821.5752043.765
9833.0632041.511 9844.552040.1329856.0382039.5779917.5642038.2969935.9642036.718
9946.8442035.1099957.7252032.4689965.9042030.9259979.4872030.4479990.3672026.796
9994.022 2024.8810001.472021.80210012.552023.69810023.622028.78310037.622033.269
10045.782036.35810056.852039.06910067.932041.06910084.122042.27910107.382044.998
10145.472047.54910167.622049.38210178.62 2050.7710222.532054.00510250.982055.387
#Mann= 3 , 0 , 0
 9749.07    0.04       0 9749.07    0.04       010250.98    0.04       0
#XS Ineff= 2 , 0
       0                               0
Bank Sta=9749.07,10250.98
Exp/Cntr=0.3,0.1

Type RM Length L Ch R = 1 , 27090.2,246.401100,246.401100,246.401100
XS GIS Cut Line= 6
714838.957769673759424.208423868 714837.66287227759587.329500082
 714838.99367227759674.189711002714839.035149952759676.189280857
714839.536184948759750.582318611  714835.1973066759926.125960563
#Sta/Elev= 30
9749.0032063.4739759.7952059.8189769.7962057.3249779.796  2052.99789.7962050.083
9809.797 2047.219819.7972044.4539879.7992039.2419959.8062034.8149969.8072032.785
9979.8082027.372 9999.812018.71410009.812026.03110019.812030.70910029.812033.207
10039.812034.47610049.812034.57310059.812033.34110069.81 2030.4310079.812026.059
10089.822023.35910109.822030.06910119.832032.51710149.842036.71310169.842038.363
10199.852038.81210209.852037.56510219.862034.47210229.862029.77910250.992035.749
#Mann= 3 , 0 , 0
9749.003    0.04       09749.003    0.04       010250.99    0.04       0
#XS Ineff= 2 , 0
       0                 10042.2       0
Bank Sta=9749.003,10250.99
Exp/Cntr=0.3,0.1

Type RM Length L Ch R = 1 , 26843.8,260.526100,260.526100,260.526100
XS GIS Cut Line= 6
714751.118371304759386.162230258714727.345316319759445.317874505
714693.342708753759507.118388575714656.244415146759556.336455834
714565.512492239759653.625853457714475.617874922759800.928745861
#Sta/Elev= 30
9749.0832057.4129758.6082055.573 9790.942055.2889801.7172049.2139812.8372047.533
9840.3382041.7569860.5372038.6579915.2442034.1629930.5162034.0099943.3712033.209
9961.1112031.342 9971.292029.4679975.3592027.4669989.6072018.819    99992015.621
   100012015.45610003.722015.48510031.932030.54710041.142032.70710047.642033.629
10067.07 2034.8110079.91 2036.6410091.912036.78710127.912038.71510151.542041.682
10163.652041.85110186.642043.74910209.632048.30810232.622052.02710250.932056.156
#Mann= 3 , 0 , 0
9749.083    0.04       09749.083    0.04       010250.93    0.04       0
#XS Ineff= 2 , 0
       0                               0
Bank Sta=9749.083,10250.93
Exp/Cntr=0.3,0.1