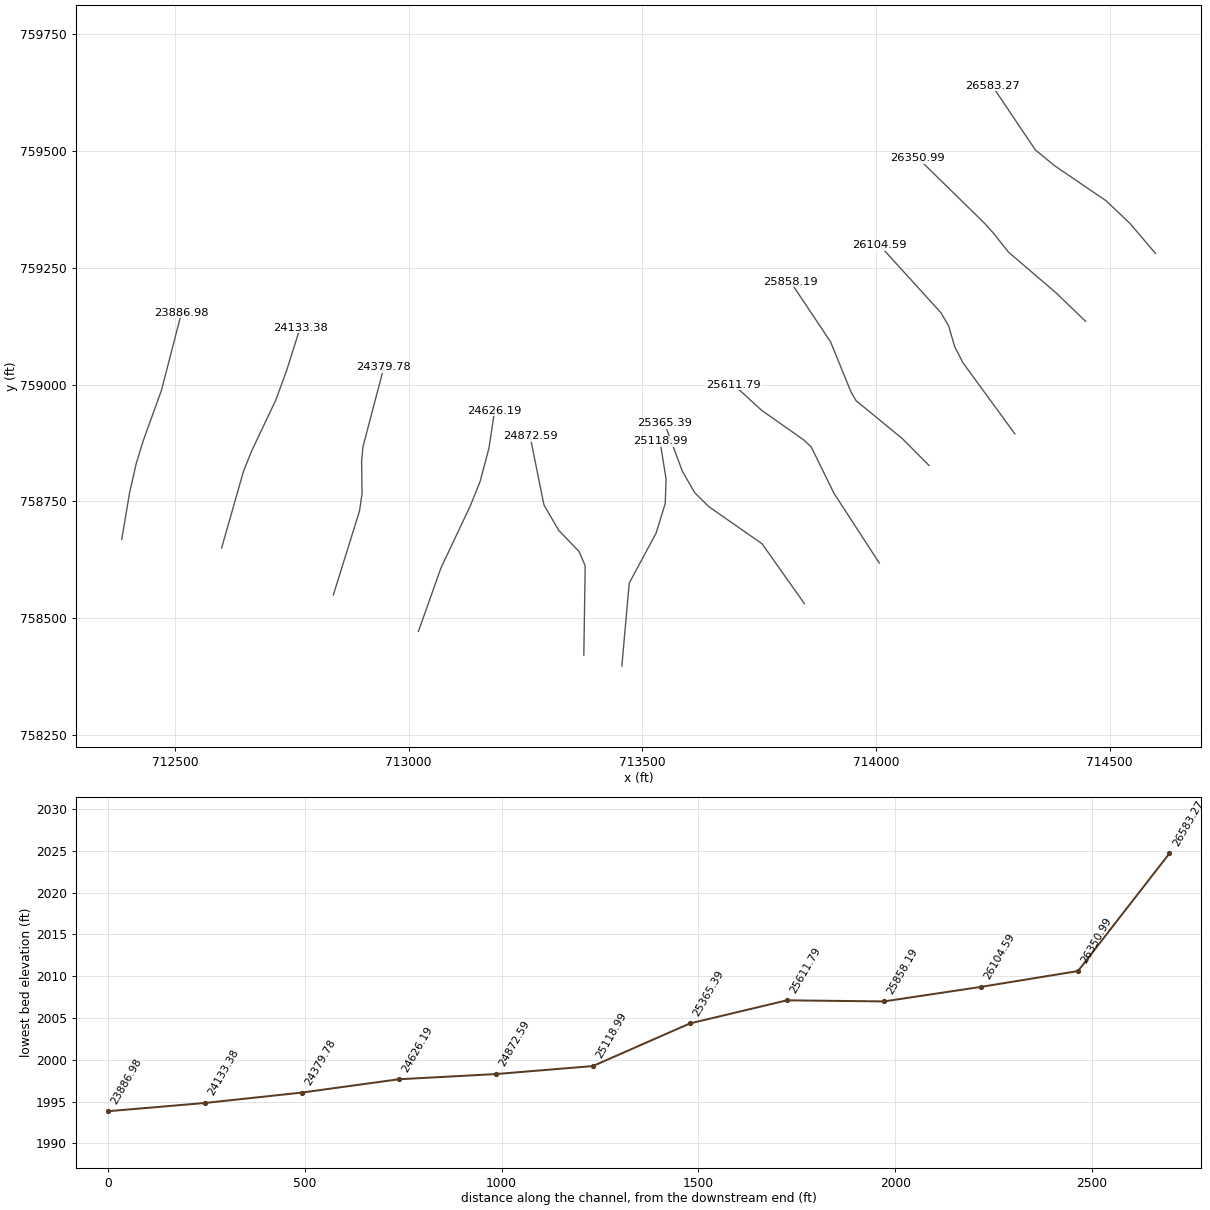
HEC-RAS study 14510_ras.prj: 14510

--- 14510_ras.g01 (geometry) --- (continued)

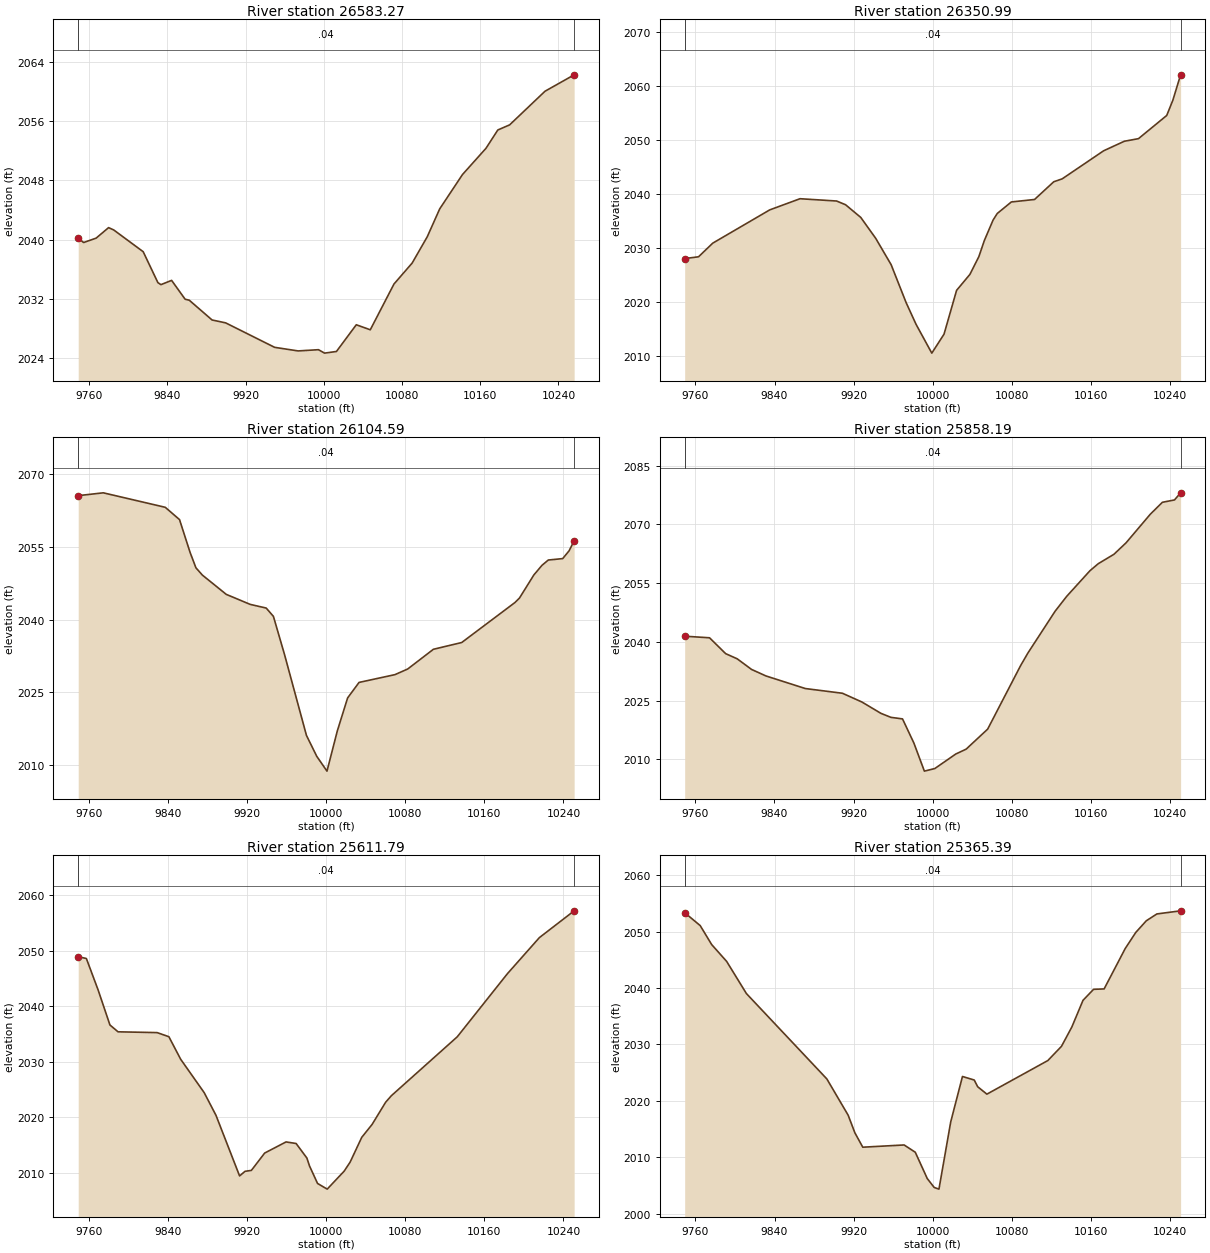
Type RM Length L Ch R = 1 ,26583.27,232.276300,232.276300,232.276300
XS GIS Cut Line= 6
714597.738737851759280.643275514714543.143363625759344.801929459
714492.313082844759393.115737185714382.128608614759468.109568819
714340.624694675759502.172337711714248.271122158759639.673198432
#Sta/Elev= 30
9748.8762040.201 9754.432039.6189767.1782040.2089779.9272041.626 9785.222041.312
9815.3132038.382 9830.362034.2139833.4412033.9399844.3882034.5149858.1852031.977
9862.4712031.8389885.7782029.1749899.574 2028.799949.7742025.4869973.7572025.004
9994.5432025.169 10000.82024.70710012.952024.93110033.232028.53210047.542027.853
10071.772034.02410090.372036.85210105.78 2040.3910118.552044.15810141.832048.783
10165.892052.32910177.962054.79110190.03 2055.4810226.232060.01610256.012062.227
#Mann= 3 , 0 , 0
9748.876    0.04       09748.876    0.04       010256.01    0.04       0
#XS Ineff= 2 , 0
       0                               0
Bank Sta=9748.876,10256.01
Exp/Cntr=0.3,0.1

Type RM Length L Ch R = 1 ,26350.99,246.401200,246.401200,246.401200
XS GIS Cut Line= 6
714448.363917189759135.277218794714385.284816239759196.018517961
714283.001119918759283.685901759714252.082076716759322.801019087
714231.311208726759345.848016998714089.358894472759484.829260925
#Sta/Elev= 30
9749.0552028.1079763.0722028.4379777.4892030.9619835.1562037.1129865.7922039.175
9902.852 2038.759911.891 2038.069927.2582035.7179942.3642031.8589957.9912026.983
9973.1182019.9839983.1932015.9589999.1492010.62210011.522014.12410024.232022.226
 10037.72025.17910046.792028.472 10052.32031.43210061.132035.21410065.382036.443
10079.672038.57810103.122039.03310122.562042.30910131.112042.84910173.092048.043
10194.032049.80310208.322050.28410236.912054.57310243.072057.37210250.962062.086
#Mann= 3 , 0 , 0
9749.055    0.04       09749.055    0.04       010250.96    0.04       0
#XS Ineff= 2 , 0
       0                               0
Bank Sta=9749.055,10250.96
Exp/Cntr=0.3,0.1

Type RM Length L Ch R = 1 ,26104.59,246.401200,246.401200,246.401200
XS GIS Cut Line= 6
714296.826661396758894.754785444714186.124230625759046.305926733
714168.116009821759081.332283681714155.459170517759125.075985744
714138.761640382759153.639047648714007.066865946759298.719114844
#Sta/Elev= 30
9749.1012065.6279774.482 2066.219837.166 2063.229851.6122060.679 9862.242053.932
9868.1922050.7289874.6662049.2299898.8972045.2369923.1282043.1669939.2852042.409
9946.6022040.6949957.8462032.8039980.0272016.1089990.4332011.794 10000.82008.727
10011.242017.02310021.682023.84710033.252027.04910069.532028.65510082.46 2029.82
10108.462033.89310137.132035.29310190.842043.53110195.512044.463 10210.12049.246
 10218.32051.229 10224.72052.32810239.292052.62610245.762054.23310250.872056.304
#Mann= 3 , 0 , 0
9749.101    0.04       09749.101    0.04       010250.87    0.04       0
#XS Ineff= 2 , 0
       0                               0
Bank Sta=9749.101,10250.87
Exp/Cntr=0.3,0.1

Type RM Length L Ch R = 1 ,25858.19,246.401200,246.401200,246.401200
XS GIS Cut Line= 6
714113.490004488758826.725784969 714056.28407262758884.319529229
713957.267564532758965.506679934713946.370658565758984.107090624
713902.594525727759091.551213867713816.776197124759220.050787082
#Sta/Elev= 30
9749.1432041.4299774.2982041.0239790.6022036.977 9802.322035.6539816.8272032.942
9831.404 2031.289871.2522028.0659908.7772026.8639928.4152024.6369947.7432021.732
 9957.822020.7129969.5482020.318 9981.052014.159 9991.662006.98610002.24 2007.65
10023.392011.34510033.962012.60410055.692017.70510089.052033.93310096.332037.103
10123.922047.79810135.692051.61310159.222058.14710167.532059.92510183.452062.338
 10195.72065.25610220.222072.55610232.482075.60910244.73 2076.2110250.922078.026
#Mann= 3 , 0 , 0
9749.143    0.04       09749.143    0.04       010250.92    0.04       0
#XS Ineff= 2 , 0
       0                               0
Bank Sta=9749.143,10250.92
Exp/Cntr=0.3,0.1

Type RM Length L Ch R = 1 ,25611.79,246.401200,246.401200,246.401200
XS GIS Cut Line= 6
714006.958568352758618.076679478713909.758424047758767.678727729
713861.294538438758866.550584366713844.894433262758881.868655284
713755.016616823758945.029389167713695.524279317758999.568841462
#Sta/Elev= 30
9749.0462048.8879757.3022048.5649769.2272042.8929781.1532036.6189789.3492035.389
9828.8542035.2489840.7792034.5119852.7052030.4639876.5562024.4499888.4812020.373
9912.3322009.4919917.8312010.3219924.2572010.4849937.7352013.6049959.3462015.603
9969.5512015.3189980.4162012.7129983.1442011.2649991.2332008.138   10001 2007.12
10018.182010.35510024.152011.95810035.962016.429 10046.4 2018.7410060.092022.726
10065.832023.89310132.58 2034.4910183.322045.82910215.682052.31510250.872057.131
#Mann= 3 , 0 , 0
9749.046    0.04       09749.046    0.04       010250.87    0.04       0
#XS Ineff= 2 , 0
       09973.289                       0
Bank Sta=9749.046,10250.87
Exp/Cntr=0.3,0.1

Type RM Length L Ch R = 1 ,25365.39,246.401200,246.401200,246.401200
XS GIS Cut Line= 6
 713846.53491416758531.467614121713756.162110272758659.352435331
713642.060773221 758738.87683917713612.090249231 758768.53900178
713585.695983254758814.401391362713547.125316304 758917.49218041
#Sta/Elev= 30
 9749.062053.347 9764.762051.0619776.3622047.6999791.5372044.709 9811.512039.016
9892.936 2023.889914.4762017.4589921.2582014.3449929.2772011.7829971.1212012.178
9982.3932010.8919994.5272006.22910001.532004.64910006.362004.35110018.26 2016.26
10030.162024.31710042.062023.68810045.562022.49710054.882021.18510116.552027.139
10130.352029.66210140.832033.08510152.152037.81810162.822039.763 10173.52039.833
10194.852046.99510205.532049.84710216.212051.91410226.882053.123 10250.92053.675
#Mann= 3 , 0 , 0
 9749.06    0.04       0 9749.06    0.04       0 10250.9    0.04       0
#XS Ineff= 2 , 0
       0                               0
Bank Sta=9749.06,10250.9
Exp/Cntr=0.3,0.1

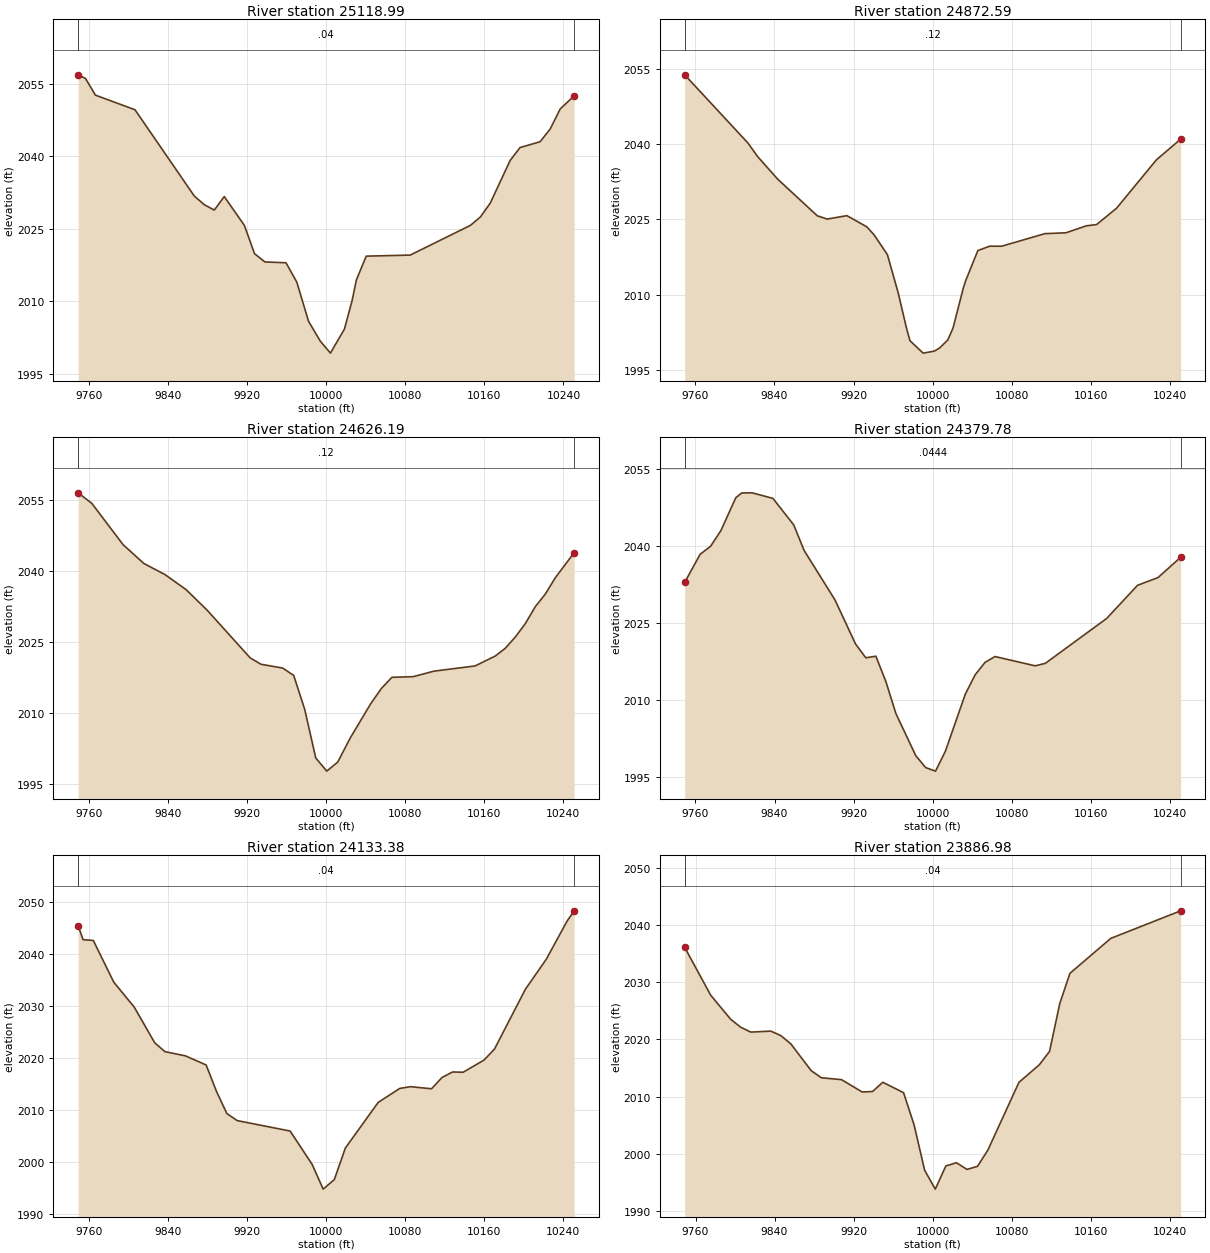
Type RM Length L Ch R = 1 ,25118.99,246.401200,246.401200,246.401200
XS GIS Cut Line= 6
713456.077497757758397.625072872713471.929916275758575.403124183
713529.443904827758682.192373778713548.966152588758745.651906663
713550.787079465758797.769299452713537.695779678758878.749939479
#Sta/Elev= 30
9749.0842056.8089756.4672056.0579766.4782052.6089806.5222049.5859866.6292031.717
9876.7052029.943 9886.78 2028.849896.856 2031.639917.2572025.6569927.4692019.827
9937.9422018.1069959.3412017.9379970.3022013.916  9982.12005.8559993.9262001.757
10004.291999.24910018.45 2004.2310026.15 2010.0710030.552014.39510040.492019.306
10085.012019.526   101462025.681   101562027.406   101662030.283 10186.12039.094
10196.162041.77110216.482042.97810226.672045.62710236.862049.77810250.872052.452
#Mann= 3 , 0 , 0
9749.084    0.04       09749.084    0.04       010250.87    0.04       0
#XS Ineff= 2 , 0
       0                               0
Bank Sta=9749.084,10250.87
Exp/Cntr=0.3,0.1

Type RM Length L Ch R = 1 ,24872.59,246.401200,246.401200,246.401200
XS GIS Cut Line= 6
713374.747426822758421.097455926713377.718599926758612.326473214
713364.563168978758642.952107064 713320.81210198758688.360755426
713289.370535478758742.721458638  713259.8426307758889.320392015
#Sta/Elev= 30
 9749.14  2053.99813.1452040.2769823.1622037.5179843.1942033.0659883.2592025.736
9893.263 2025.08 9913.27 2025.769933.4712023.5229940.8812021.9019954.2442017.964
9965.2552010.2629973.4552003.3719977.0462000.7769990.3741998.29110001.581998.684
10007.011999.31610015.262000.89310020.612003.28810031.152011.38910033.472012.788
10045.76 2018.7910057.762019.66210069.762019.65110113.622022.16510134.882022.336
10155.512023.73210165.822023.97210186.072027.24410226.452036.92910250.882041.043
#Mann= 3 , 0 , 0
 9749.14    0.12       0 9749.14    0.12       010250.88    0.12       0
#XS Ineff= 2 , 0
       0                               0
Bank Sta=9749.14,10250.88
Exp/Cntr=0.3,0.1

Type RM Length L Ch R = 1 ,24626.19,246.401200,246.401200,246.401200
XS GIS Cut Line= 6
713020.880156587758471.913442457713068.968158723 758607.34138189
713132.466582283 758741.82675119 713152.91830755758792.894078615
713171.814406989758864.106887693713183.884007673758943.886423466
#Sta/Elev= 30
9749.0212056.4479762.7982054.2229794.3792045.5169815.4342041.529 9836.712039.198
9858.1332036.0179879.5572031.6529923.046 2021.599933.991 2020.249955.9732019.433
9967.1242017.8799978.274  2010.79989.4252000.45810000.581997.669 10011.71999.583
10024.432004.70710044.942011.86510055.712015.08910066.492017.47810088.032017.619
 10109.2 2018.7910150.632019.88110171.162021.98210181.272023.61410191.552026.039
 10201.52028.82110211.612032.39910221.722035.04610231.842038.50510250.942043.805
#Mann= 3 , 0 , 0
9749.021    0.12       09749.021    0.12       010250.94    0.12       0
#XS Ineff= 2 , 0
       0                               0
Bank Sta=9749.021,10250.94
Exp/Cntr=0.3,0.1

Type RM Length L Ch R = 1 ,24379.78,246.401200,246.401200,246.401200
XS GIS Cut Line= 6
712838.941798978758550.121155616712894.854167359758729.541810957
712900.323520787758767.207562204712899.335854681758836.754401787
712902.398712247758867.608167094712946.960930189759036.977898538
#Sta/Elev= 30
9749.0632032.9189764.7172038.3989775.2382039.9559785.7592043.0349800.7452049.433
  9806.82050.3739817.3212050.3999838.3622049.3169859.4042044.1439869.925 2039.15
9901.2042029.4829921.9522020.9019932.3252018.2049942.5522018.5039952.6572013.568
9962.7622007.3449982.893  1999.19992.8971996.76810002.931996.07510012.941999.986
10032.962011.05110042.982014.87510053.022017.29910063.072018.44210103.792016.627
10114.032017.11510176.152025.88510207.322032.343 10228.12033.86210250.932037.815
#Mann= 3 , 0 , 0
9749.063  0.0444       09749.063  0.0444       010250.93  0.0444       0
#XS Ineff= 2 , 0
       0                               0
Bank Sta=9749.063,10250.93
Exp/Cntr=0.3,0.1

Type RM Length L Ch R = 1 ,24133.38,246.401100,246.401100,246.401100
XS GIS Cut Line= 6
712599.775080378758650.230310215712646.687794751758814.641830033
712663.594890813758856.849144606712715.972009959758967.359649456
712739.017745233759030.292621769 712767.92422165759121.936528552
#Sta/Elev= 30
9749.036 2045.479753.9722042.8099764.3212042.6559785.0192034.6429805.7172029.844
9826.415 2022.999836.7642021.2719857.5632020.4629878.5162018.7059888.9922013.621
9899.4692009.3679909.945 2008.019963.5222005.9999985.7971999.5879996.9721994.828
 10008.21996.65510019.412002.727 10052.6  2011.510074.392014.18610085.292014.534
10106.652014.12910117.292016.30610127.942017.36310138.592017.30610159.822019.662
 10170.32021.75110201.762033.31310222.732039.031 10243.72046.33710250.972048.355
#Mann= 3 , 0 , 0
9749.036    0.04       09749.036    0.04       010250.97    0.04       0
#XS Ineff= 2 , 0
       0                               0
Bank Sta=9749.036,10250.97
Exp/Cntr=0.3,0.1

Type RM Length L Ch R = 1 ,23886.98,246.401200,246.401200,246.401200
XS GIS Cut Line= 6
712386.224355174758669.023725652712402.837167079758768.082920262
712417.091232216 758830.81649443712432.367401044758880.552427939
 712471.15332056758987.852788437712513.898025249759153.435758736
#Sta/Elev= 30
9749.0382036.1169775.3772027.7439795.6562023.5249805.7962022.1429815.9352021.295
9836.2152021.4669846.3542020.6869856.5742019.2199877.0832014.5529887.3382013.315
9907.8482012.975 9928.65 2010.839939.1112010.9019949.5722012.5229970.5882010.701
9981.2592005.054 9991.931997.13110002.661993.84110013.361997.88910024.061998.459
10034.771997.29110045.351997.81810055.892000.65810087.352012.508   101082015.585
10118.33 2017.9210128.662026.28110138.992031.574 10180.32037.67710250.982042.495
#Mann= 3 , 0 , 0
9749.038    0.04       09749.038    0.04       010250.98    0.04       0
#XS Ineff= 2 , 0
       0                               0
Bank Sta=9749.038,10250.98
Exp/Cntr=0.3,0.1