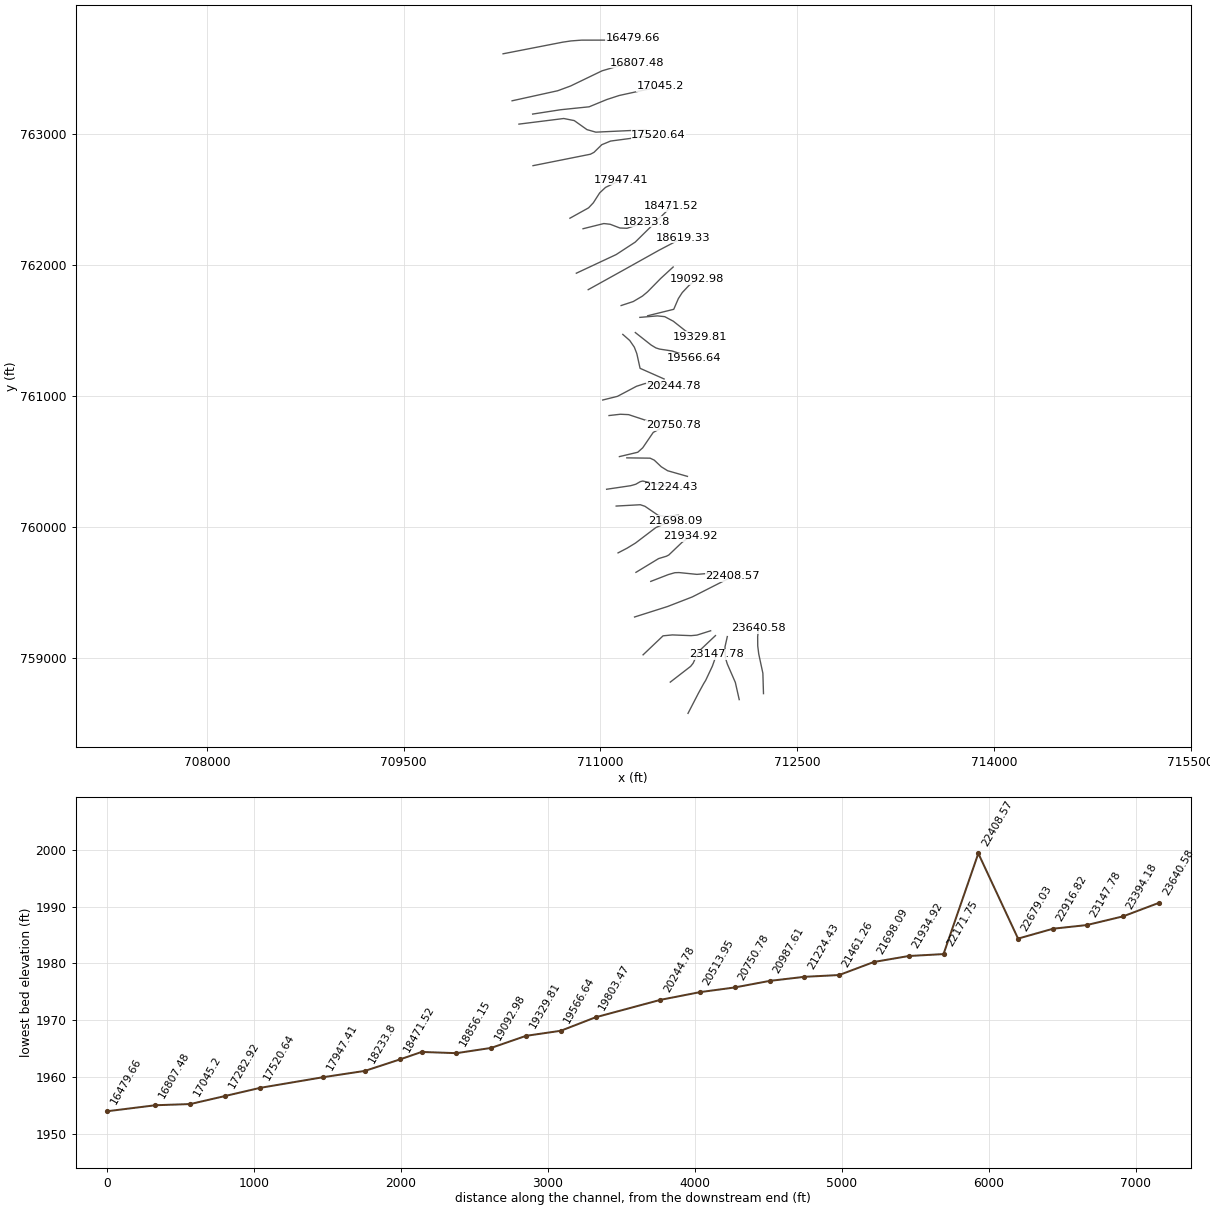
HEC-RAS study 14510_ras.prj: 14510

--- 14510_ras.g01 (geometry) --- (continued)

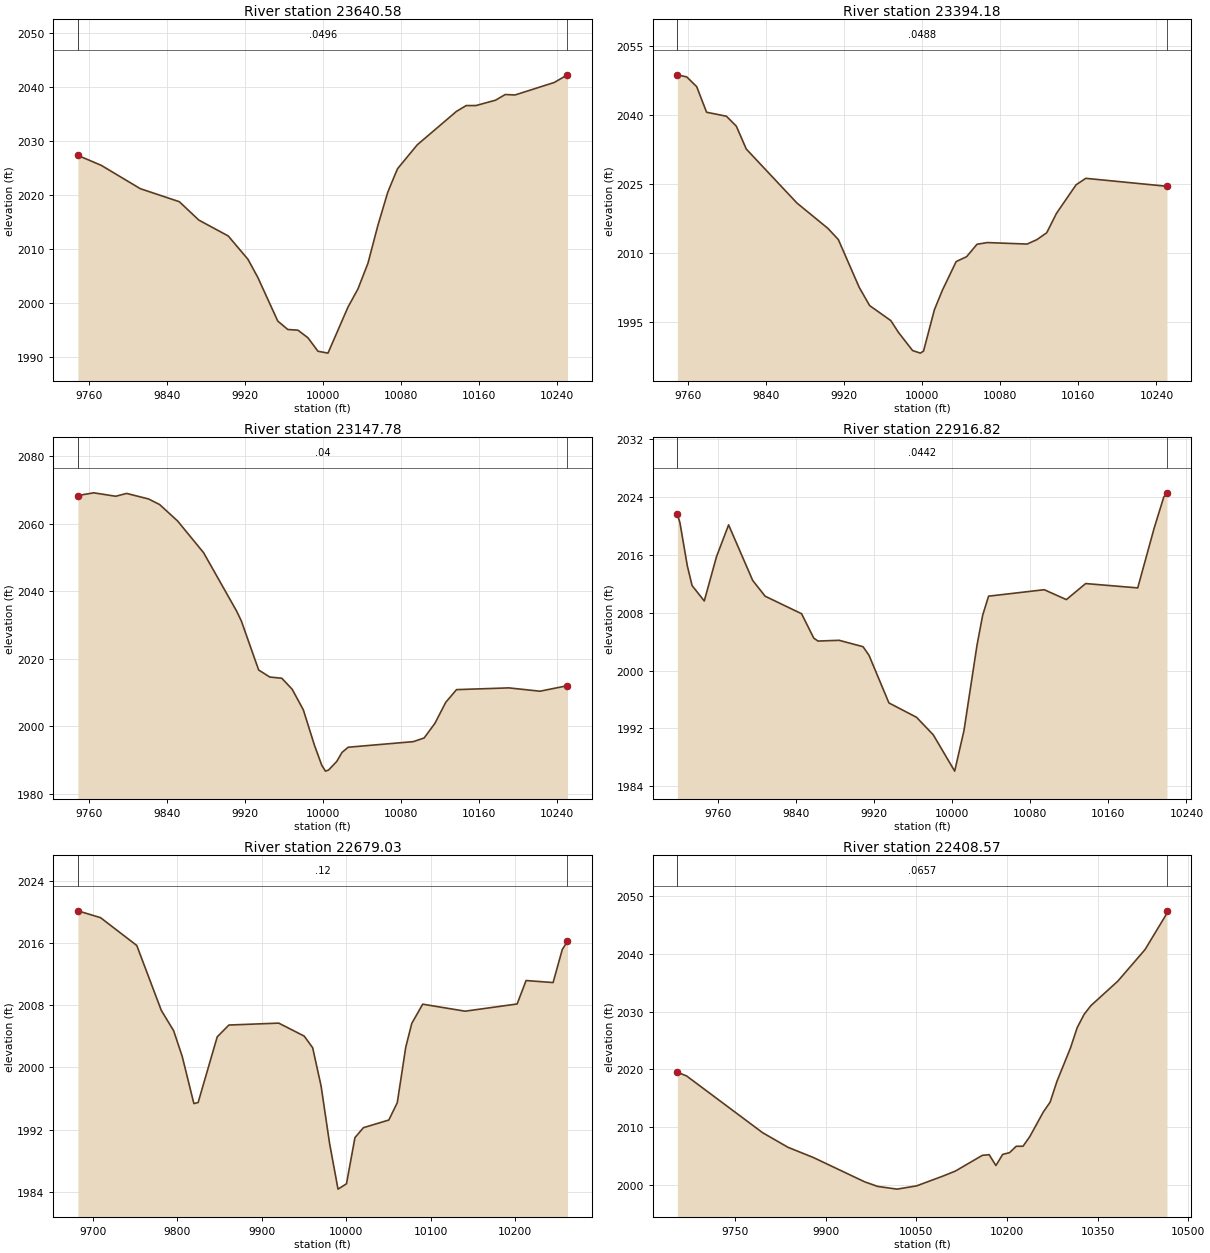
Type RM Length L Ch R = 1 ,23640.58,246.401200,246.401200,246.401200
XS GIS Cut Line= 6
712243.611256934758731.052764893712238.938518953758886.443345774
712207.394827112759033.362838676712199.794973981759094.545687753
712199.128790558759165.095791531712205.673532565759228.510350578
#Sta/Elev= 30
 9749.052027.2639772.9972025.4249812.9982021.1099853.0272018.6959873.072 2015.29
 9903.142012.3589923.3872008.0389933.5182004.6779953.9311996.6099964.2371995.049
9974.5421994.9329984.8481993.5239995.1541991.02510005.411990.67710025.891999.183
10036.132002.56210046.372007.30310056.582014.32510066.662020.43510074.362023.808
10076.742024.80310096.89 2029.2210137.062035.40210147.062036.48510157.072036.489
10177.072037.47310187.082038.52610197.132038.44510237.342040.75810250.922042.173
#Mann= 3 , 0 , 0
 9749.05  0.0496       0 9749.05  0.0496       010250.92  0.0496       0
#XS Ineff= 2 , 0
       0                               0
Bank Sta=9749.05,10250.92
Exp/Cntr=0.3,0.1

Type RM Length L Ch R = 1 ,23394.18,246.401200,246.401200,246.401200
XS GIS Cut Line= 6
712058.599594488758685.517034648712028.922313938758816.725403617
711967.413580916758957.734959617711952.712031203759005.480087701
711950.065454159759087.513326724711967.762242714759166.123988414
#Sta/Elev= 30
9749.1022048.652 9758.732048.1979768.8832046.0879779.0362040.5369799.3422039.671
9809.4952037.5219819.708 2032.559871.6142020.8429903.3412015.3449914.0422012.916
9935.443 2002.559946.143 1998.599967.7811995.3439975.6921992.7679990.1271988.841
9998.1111988.27810001.36 1988.73 10012.51997.69710020.572001.87410034.772008.134
10045.522009.20310056.122011.89110066.712012.26310107.472011.93910117.542012.899
 10127.62014.39610137.62 2018.6110157.642024.78610167.652026.19910250.842024.469
#Mann= 3 , 0 , 0
9749.102  0.0488       09749.102  0.0488       010250.84  0.0488       0
#XS Ineff= 2 , 0
       0                               0
Bank Sta=9749.102,10250.84
Exp/Cntr=0.3,0.1

Type RM Length L Ch R = 1 ,23147.78,230.956500,230.956500,230.956500
XS GIS Cut Line= 6
711668.062941847758580.560729064711747.521519833758734.284641378
711787.776326224758807.869251631 711802.72937202758832.124928696
711853.734808384758940.285124617711886.066304459759031.585560845
#Sta/Elev= 30
9749.0222068.4019765.276  2069.2 9787.792068.1859799.0472069.0229821.5612067.372
9832.8182065.7289851.2422060.8579877.8452051.4739911.6162034.2239916.576 2031.24
9934.3282016.7129945.7712014.626 9958.032014.2719968.6552011.0199980.0982004.925
 9991.541994.405    99991988.50810002.781986.75110005.971987.07510014.351989.621
10019.741992.284 10026.11993.83110092.93 1995.4910103.98 1996.5810115.042000.932
 10126.12007.13710137.152010.89710190.882011.411 10222.72010.42810250.912012.069
#Mann= 3 , 0 , 0
9749.022    0.04       09749.022    0.04       010250.91    0.04       0
#XS Ineff= 2 , 0
       0                               0
Bank Sta=9749.022,10250.91
Exp/Cntr=0.3,0.1

Type RM Length L Ch R = 1 ,22916.82,237.792700,237.792700,237.792700
XS GIS Cut Line= 6
711532.908723799758818.925521995711688.167103007758939.023196882
 711707.20991877  758963.0114977711734.288975935759022.443220132
711765.332182819759067.789019575711877.484000574759173.695143422
#Sta/Elev= 30
9718.2652021.6119720.873 2020.469728.435  2014.59733.3412011.7639745.8092009.634
9758.2782015.7339770.7462020.1599795.4042012.4849808.1522010.2959845.5572007.868
9858.0252004.4969862.373 2004.099884.0082004.1959908.5052003.3129914.6512002.119
 9935.051995.5359963.3591993.5459980.5211991.11910002.441986.10110011.971991.722
10025.322003.52410031.142007.67110037.152010.297 10094.22011.19110116.892009.825
10136.672012.04310190.022011.44210206.872019.709 10216.72024.00410220.012024.591
#Mann= 3 , 0 , 0
9718.265  0.0442       09718.265  0.0442       010220.01  0.0442       0
#XS Ineff= 2 , 0
       0                               0
Bank Sta=9718.265,10220.01
Exp/Cntr=0.3,0.1

Type RM Length L Ch R = 1 ,22679.03,270.454400,270.454400,270.454400
XS GIS Cut Line= 6
711325.592373788759027.012336731711477.930605769759171.871710241
 711548.81648308759178.781472579711691.856139749759173.202201128
711735.975671589759177.314351887711840.684828222759210.357940108
#Sta/Elev= 30
 9682.642020.1099709.4222019.2319752.2792015.6619781.3032007.3219795.8142004.727
9806.0172001.4159819.8161995.3589824.8381995.4919847.4152003.9229861.2142005.442
9920.1762005.6899950.2812004.0239960.3012002.5319970.3091997.5969980.3091990.238
9990.3091984.36910000.311985.05910010.311990.98110020.32 1992.2610050.381993.243
10060.391995.47310070.412002.59810077.52 2005.6510090.452008.12110140.622007.221
10202.132008.14610212.722011.15610244.672010.89810255.532015.142 10261.72016.212
#Mann= 3 , 0 , 0
 9682.64    0.12       0 9682.64    0.12       0 10261.7    0.12       0
#XS Ineff= 2 , 0
       09904.921                       0
Bank Sta=9682.64,10261.7
Exp/Cntr=0.3,0.1

Type RM Length L Ch R = 1 ,22408.57,236.828000,236.828000,236.828000
XS GIS Cut Line= 4
711260.506726444759315.354464367711511.739049911759395.137702227
711700.163292468759468.130877256712007.413633943759624.302321553
#Sta/Elev= 30
9654.5222019.5249669.7292018.8889795.6342009.0799837.6032006.5589879.5712004.795
9964.5122000.593 9985.961999.80210018.131999.33410050.311999.891 10093.22001.553
10114.652002.45310159.272005.17110170.482005.285 10181.72003.41210192.922005.337
10204.142005.62810215.352006.73810226.572006.74310237.79 2008.4110260.222012.665
10271.442014.35910282.662017.93410305.092023.71710316.312027.24810327.532029.499
10338.752031.01410383.622035.27910428.492040.70910462.142046.52610464.852047.408
#Mann= 3 , 0 , 0
9654.522  0.0657       09654.522  0.0657       010464.85  0.0657       0
#XS Ineff= 2 , 0
       0                               0
Bank Sta=9654.522,10464.85
Exp/Cntr=0.3,0.1

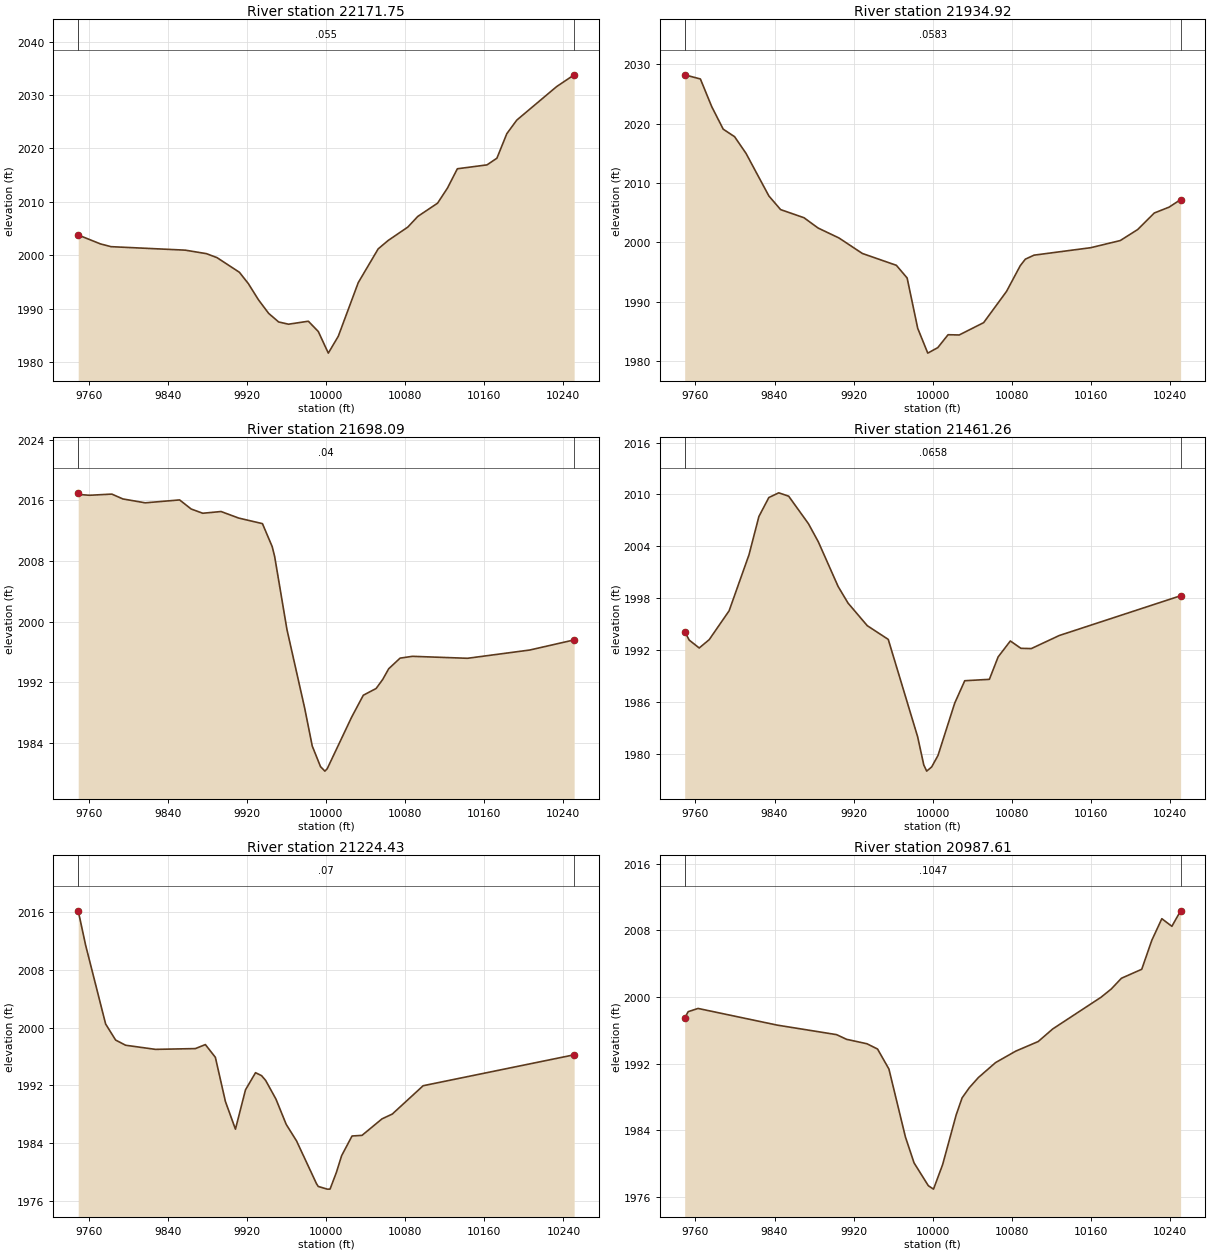
Type RM Length L Ch R = 1 ,22171.75,236.828000,236.828000,236.828000
XS GIS Cut Line= 6
711384.012095749759586.818106552711519.564356067759639.334352791
711568.248761251759653.131980697711599.233108981 759654.15924942
711736.104866777759640.380770642711872.607660406 759651.73544266
#Sta/Elev= 30
9749.1042003.7829771.612 2002.119782.3362001.5949857.4062000.9419878.8542000.284
9889.5781999.5369912.2231996.792 9921.281994.6619931.5421991.6279941.8031989.095
9951.8921987.4919961.8971987.0679981.9611987.6259992.0581985.69410002.171981.647
10012.271984.81110032.451994.84910052.632001.18210062.652002.74310082.682005.272
10092.692007.25710112.722009.74210122.73 2012.5710132.742016.18910162.762016.917
10172.772018.17310182.78 2022.7610192.862025.30510233.172031.58210250.92 2033.79
#Mann= 3 , 0 , 0
9749.104   0.055       09749.104   0.055       010250.92   0.055       0
#XS Ineff= 2 , 0
       0                               0
Bank Sta=9749.104,10250.92
Exp/Cntr=0.3,0.1

Type RM Length L Ch R = 1 ,21934.92,236.828000,236.828000,236.828000
XS GIS Cut Line= 6
711271.226894639759655.860518157711444.015289053759760.768903609
711503.465124053759778.786637329711521.700819897759788.218142152
711623.340028036759885.303519014711684.788825375759929.490765743
#Sta/Elev= 30
9749.136 2028.219765.0252027.513 9776.562022.8299788.0962019.0589799.6322017.782
9811.168 2014.989834.3662007.7849846.1772005.498  9869.82004.1319884.101 2002.39
9905.2342000.7159928.8561998.1079963.2761996.1099974.1641993.9769984.8711985.496
9995.047 1981.31 10005.21982.23910015.581984.41210026.841984.36810051.561986.447
10074.681991.70310088.591996.04310093.771997.14710102.511997.81910159.871999.076
10189.782000.28110207.412002.14110224.182004.92510239.162005.91210250.822007.182
#Mann= 3 , 0 , 0
9749.136  0.0583       09749.136  0.0583       010250.82  0.0583       0
#XS Ineff= 2 , 0
       0                               0
Bank Sta=9749.136,10250.82
Exp/Cntr=0.3,0.1

Type RM Length L Ch R = 1 ,21698.09,236.828000,236.828000,236.828000
XS GIS Cut Line= 6
711134.840996614759804.246064924711203.480911462 759840.02617394
711267.781469034 759879.26197486711422.702692789759997.035014883
711476.066198083760020.441419426711567.931078698760048.603096478
#Sta/Elev= 30
9749.0442016.9759750.6752016.7479760.5012016.6539783.0552016.8079794.3322016.165
9816.8862015.6569851.6592016.0399863.3732014.8399875.088 2014.289893.5942014.509
9911.4982013.6449935.494 2012.919945.3832009.8689947.8822008.551 9960.271998.955
 9978.231988.5699985.8781983.5819994.2331980.8599998.6861980.264   100011980.572
10025.761987.38810037.571990.27610050.541991.16610057.181992.35510063.271993.769
10074.771995.16910087.281995.40810142.991995.14810206.031996.23910250.931997.574
#Mann= 3 , 0 , 0
9749.044    0.04       09749.044    0.04       010250.93    0.04       0
#XS Ineff= 2 , 0
       0                               0
Bank Sta=9749.044,10250.93
Exp/Cntr=0.3,0.1

Type RM Length L Ch R = 1 ,21461.26,236.828100,236.828100,236.828100
XS GIS Cut Line= 6
711120.404188799760161.291497184711304.413599418760171.345687201
 711339.78080218760159.486475703711441.725805799760089.830522216
711499.388648489760082.111456481711594.996821652760090.743001021
#Sta/Elev= 30
9749.125 1994.129753.7581993.1369763.8391992.228 9773.921993.1899794.0821996.532
9814.1872003.0199824.2242007.4579834.2612009.6489844.2992010.1939854.3362009.804
 9874.352006.6149884.3542004.5149904.3721999.3479914.3981997.4249933.8621994.808
9955.0681993.2229984.8041981.946 9991.031978.6779993.9631977.968    99991978.456
10005.39 1979.7810022.291985.83810032.441988.43410057.381988.59710066.221991.191
10078.581993.03810089.281992.18710099.811992.15810128.071993.67110250.841998.275
#Mann= 3 , 0 , 0
9749.125  0.0658       09749.125  0.0658       010250.84  0.0658       0
#XS Ineff= 2 , 0
       0                               0
Bank Sta=9749.125,10250.84
Exp/Cntr=0.3,0.1

Type RM Length L Ch R = 1 ,21224.43,236.828000,236.828000,236.828000
XS GIS Cut Line= 6
711047.511496042760289.380195795711231.048168701760316.475203969
711269.940173559760327.678713844711304.581817686760347.638680394
711323.235238155760351.956824757711534.281420303760304.851445335
#Sta/Elev= 30
9749.0672016.1329756.6242011.3539776.8082000.486  9786.91998.2699796.9911997.549
9827.2661996.9779867.6331997.0849877.725 1997.649887.8371995.8779897.9981989.779
9908.1591985.944 9918.32 1991.389928.4821993.7539934.6271993.342 9938.741992.681
9949.146  1990.19959.553  1986.6 9969.961984.3259990.2011978.3969991.9141978.027
   100011977.65410003.861977.65410010.221979.93210015.621982.28810026.12    1985
10036.211985.08510056.441987.36710066.861988.03310098.091991.95110250.871996.227
#Mann= 3 , 0 , 0
9749.067    0.07       09749.067    0.07       010250.87    0.07       0
#XS Ineff= 2 , 0
       09938.991                       0
Bank Sta=9749.067,10250.87
Exp/Cntr=0.3,0.1

Type RM Length L Ch R = 1 ,20987.61,236.828000,236.828000,236.828000
XS GIS Cut Line= 6
711201.488279718760528.708794266711379.071736525760526.405931669
711410.525329886760511.535520673 711464.29338155760460.731929454
711512.578443182760430.630636223711663.704286819760387.517367593
#Sta/Elev= 30
9749.0971997.4679752.613 1998.249762.6251998.6299842.6931996.6289902.7471995.485
9912.9221994.9229933.5921994.3889944.2731993.7559955.7791991.3499972.4671983.202
9981.2221980.0839995.6491977.34610000.881976.93610010.081979.86810023.811985.842
10029.811987.891 10037.11989.11110046.261990.32910063.751992.13310084.141993.508
10106.791994.65410121.55 1996.1710170.411999.97310180.722000.96110191.032002.253
 10211.62003.33310221.762006.80610231.922009.40510242.082008.49110250.932010.349
#Mann= 3 , 0 , 0
9749.097  0.1047       09749.097  0.1047       010250.93  0.1047       0
#XS Ineff= 2 , 0
       0                               0
Bank Sta=9749.097,10250.93
Exp/Cntr=0.3,0.1

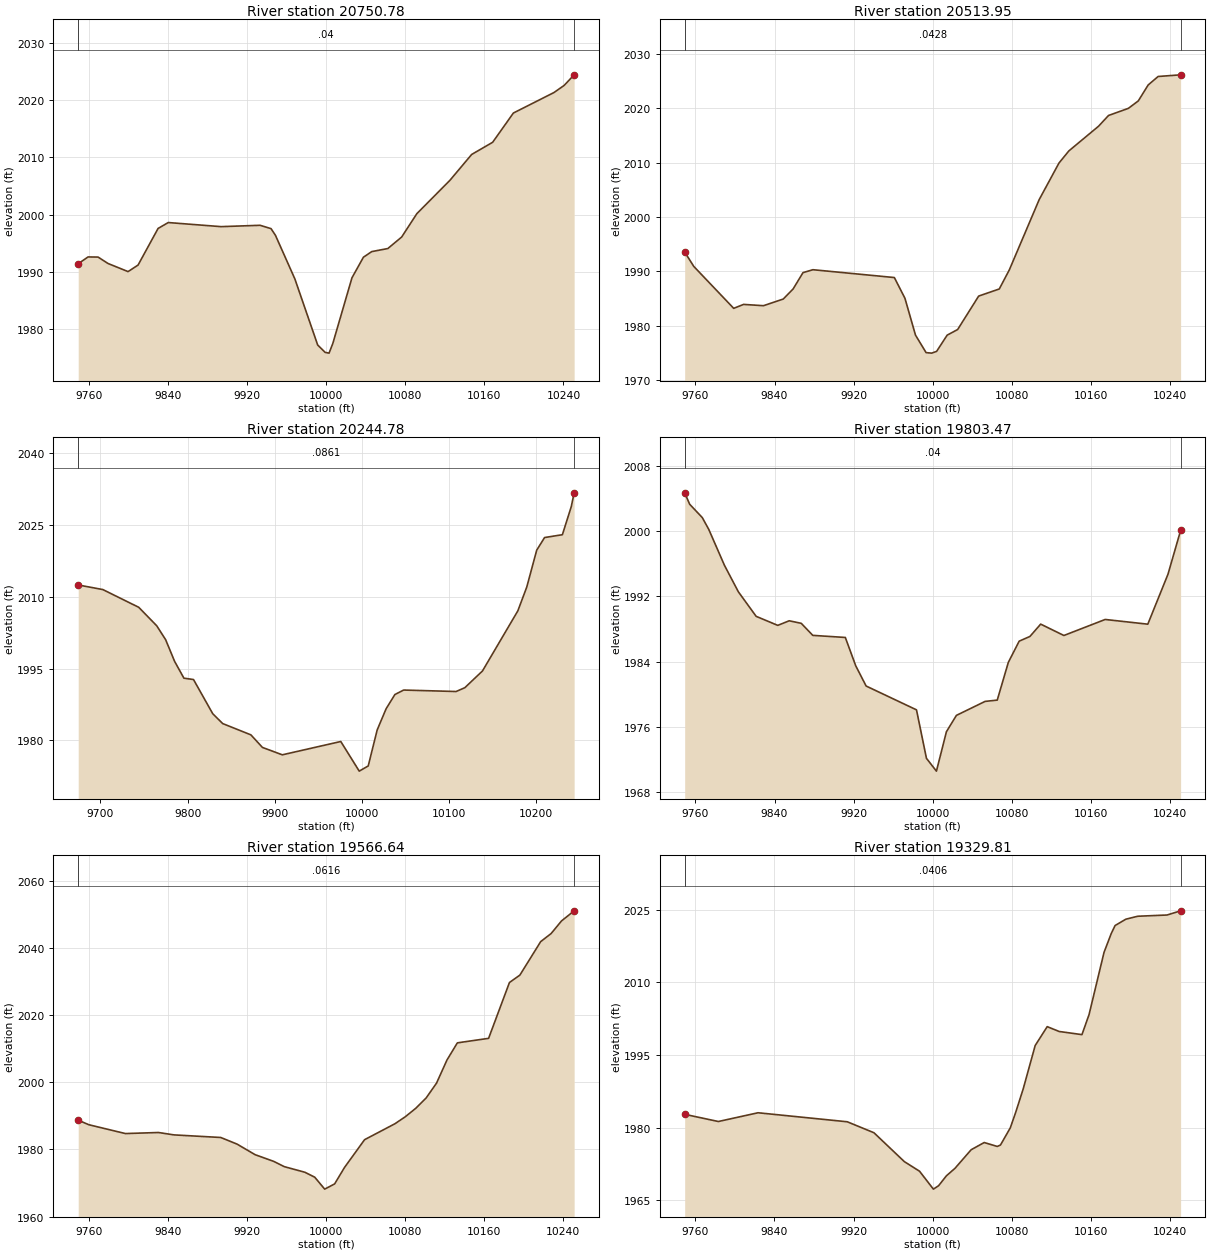
Type RM Length L Ch R = 1 ,20750.78,236.828000,236.828000,236.828000
XS GIS Cut Line= 6
711145.153146991760538.353875772711285.239519017 760571.58019013
711322.985542541760605.627308795711402.947954596760722.723088057
711460.423757425 760753.76557467711554.905961673  760778.2909111
#Sta/Elev= 30
9749.1681991.4129759.1321992.6019769.2521992.5789779.3711991.452 9799.611990.038
 9809.731991.1849829.9691997.583 9840.261998.6129893.7081997.8979933.1361998.133
9944.227 1997.55 9948.721996.3749968.3051988.7759991.4141977.209    99991975.915
10002.921975.78710006.731977.47610026.11 1988.96 10037.71992.55410046.111993.534
10062.391994.07110076.351996.07710091.742000.16610125.222006.00110147.182010.513
10168.422012.643 10189.42017.758 10230.52021.34510240.732022.58310250.862024.435
#Mann= 3 , 0 , 0
9749.168    0.04       09749.168    0.04       010250.86    0.04       0
#XS Ineff= 2 , 0
       09913.349                       0
Bank Sta=9749.168,10250.86
Exp/Cntr=0.3,0.1

Type RM Length L Ch R = 1 ,20513.95,269.167000,269.167000,269.167000
XS GIS Cut Line= 6
711065.886895513760851.340875796711152.012799746760861.262454054
711215.117488718 760858.35767363711362.839116161760809.468323478
711403.705963499760801.963914974711557.647491932760811.786435469
#Sta/Elev= 30
9749.0981993.5549758.3061990.9049798.6931983.1959808.7271983.9189828.796 1983.68
 9848.821984.902 9858.821986.756 9868.821989.7579878.8611990.2949961.2671988.855
9971.9711985.0499982.6741978.2699993.3781975.055    99991974.96310004.051975.288
10014.691978.26610025.321979.30210046.591985.44910067.441986.75410077.641990.278
10107.82 2003.1810127.822009.89210137.822012.12510167.932016.67410177.982018.643
10198.062019.952 10208.12021.32110218.142024.25710228.19 2025.8110250.932026.115
#Mann= 3 , 0 , 0
9749.098  0.0428       09749.098  0.0428       010250.93  0.0428       0
#XS Ineff= 2 , 0
       0 9908.74                       0
Bank Sta=9749.098,10250.93
Exp/Cntr=0.3,0.1

Type RM Length L Ch R = 1 ,20244.78,441.317000,441.317000,441.317000
XS GIS Cut Line= 6
711017.579948902 760969.74436304711130.181325763760997.739593953
711275.582923919761074.593417957711341.332387209761095.712055817
711433.153904229761099.678592518711558.220345199    761076.03937
#Sta/Elev= 30
9674.4472012.4529702.7022011.491 9743.922007.7899764.5292003.9459774.833 2001.02
9785.137 1996.499795.7861993.0019806.8041992.7169828.8911985.5799840.2961983.528
9872.6541981.1759885.9141978.5539908.7231977.0099975.8461979.7889997.0251973.607
10007.341974.68910017.651982.21810027.881986.61910037.951989.58910048.031990.523
10108.221990.21910118.251991.01910138.481994.50610179.072007.046 10189.32012.003
10200.732019.70710209.752022.344 10230.22022.93610240.422028.80410243.712031.675
#Mann= 3 , 0 , 0
9674.447  0.0861       09674.447  0.0861       010243.71  0.0861       0
#XS Ineff= 2 , 0
       0                               0
Bank Sta=9674.447,10243.71
Exp/Cntr=0.3,0.1

Type RM Length L Ch R = 1 ,19803.47,236.828000,236.828000,236.828000
XS GIS Cut Line= 6
711171.010868078761470.018258086711223.792823003761423.643840828
711258.856501274761372.595667115711277.885253449761323.359089926
711302.640376965761211.414187988711485.884156192761130.320639353
#Sta/Elev= 30
9749.1112004.7119754.1782003.306 9766.882001.6799773.4662000.2299789.3491995.814
9803.4681992.5529821.4461989.5469843.2961988.4399854.8691989.0029867.0371988.691
9878.7381987.2119911.6411986.9549922.1621983.4819932.6831980.9939983.6511978.068
9993.7341972.11610003.821970.54510013.931975.38110024.041977.38910053.071979.105
10065.351979.26410076.581983.90110087.561986.50210098.43 1987.0810109.311988.593
10132.791987.19610174.561989.16410217.681988.58410238.111994.72110250.882000.093
#Mann= 3 , 0 , 0
9749.111    0.04       09749.111    0.04       010250.88    0.04       0
#XS Ineff= 2 , 0
       0                               0
Bank Sta=9749.111,10250.88
Exp/Cntr=0.3,0.1

Type RM Length L Ch R = 1 ,19566.64,236.828100,236.828100,236.828100
XS GIS Cut Line= 6
711266.364230322761484.118852663711387.560197578761388.544328419
 711423.14368003761367.104034413 711450.46833995761358.277214224
 711547.84237587761343.460091787711717.115677056761287.083241459
#Sta/Elev= 30
9749.1341988.7299759.8091987.3739796.8931984.7389830.389 1985.059846.1361984.337
9893.3771983.5689909.9311981.5869928.086 1978.459947.0951976.4329957.604 1974.88
9978.4181973.2129988.4771971.7289998.5371968.17710008.581969.72910018.631974.651
10038.881982.90810069.611987.66410080.071989.74310090.61 1992.2510101.151995.337
10111.691999.75910122.232006.64210132.772011.76810164.392013.11610185.472029.749
10196.012031.95610217.092041.94310227.632044.34710238.17 2048.1110250.942051.118
#Mann= 3 , 0 , 0
9749.134  0.0616       09749.134  0.0616       010250.94  0.0616       0
#XS Ineff= 2 , 0
       0                               0
Bank Sta=9749.134,10250.94
Exp/Cntr=0.3,0.1

Type RM Length L Ch R = 1 ,19329.81,236.828000,236.828000,236.828000
XS GIS Cut Line= 6
711301.047515794761599.851216569711435.308083608761611.199336081
711490.795729762761605.269522396711555.979143169761570.630330007
711651.681039201761494.850164032711757.185633683761450.384182478
#Sta/Elev= 30
9749.147 1982.749783.2211981.2549823.363 1983.069913.6041981.1989940.5911978.935
9971.4221972.9569986.7371970.98510000.751967.28410005.991967.98410013.911970.033
10022.561971.57810038.981975.42610052.161976.91110065.341976.10310068.621976.397
10078.521979.93510083.97 1983.1210091.581987.97710103.731996.95710115.882000.852
10128.031999.85210151.031999.20310158.21 2003.3410173.382016.20610180.612020.064
10184.552021.73810195.422023.05110207.43 2023.6610237.132023.91610250.84 2024.78
#Mann= 3 , 0 , 0
9749.147  0.0406       09749.147  0.0406       010250.84  0.0406       0
#XS Ineff= 2 , 0
       0                               0
Bank Sta=9749.147,10250.84
Exp/Cntr=0.3,0.1

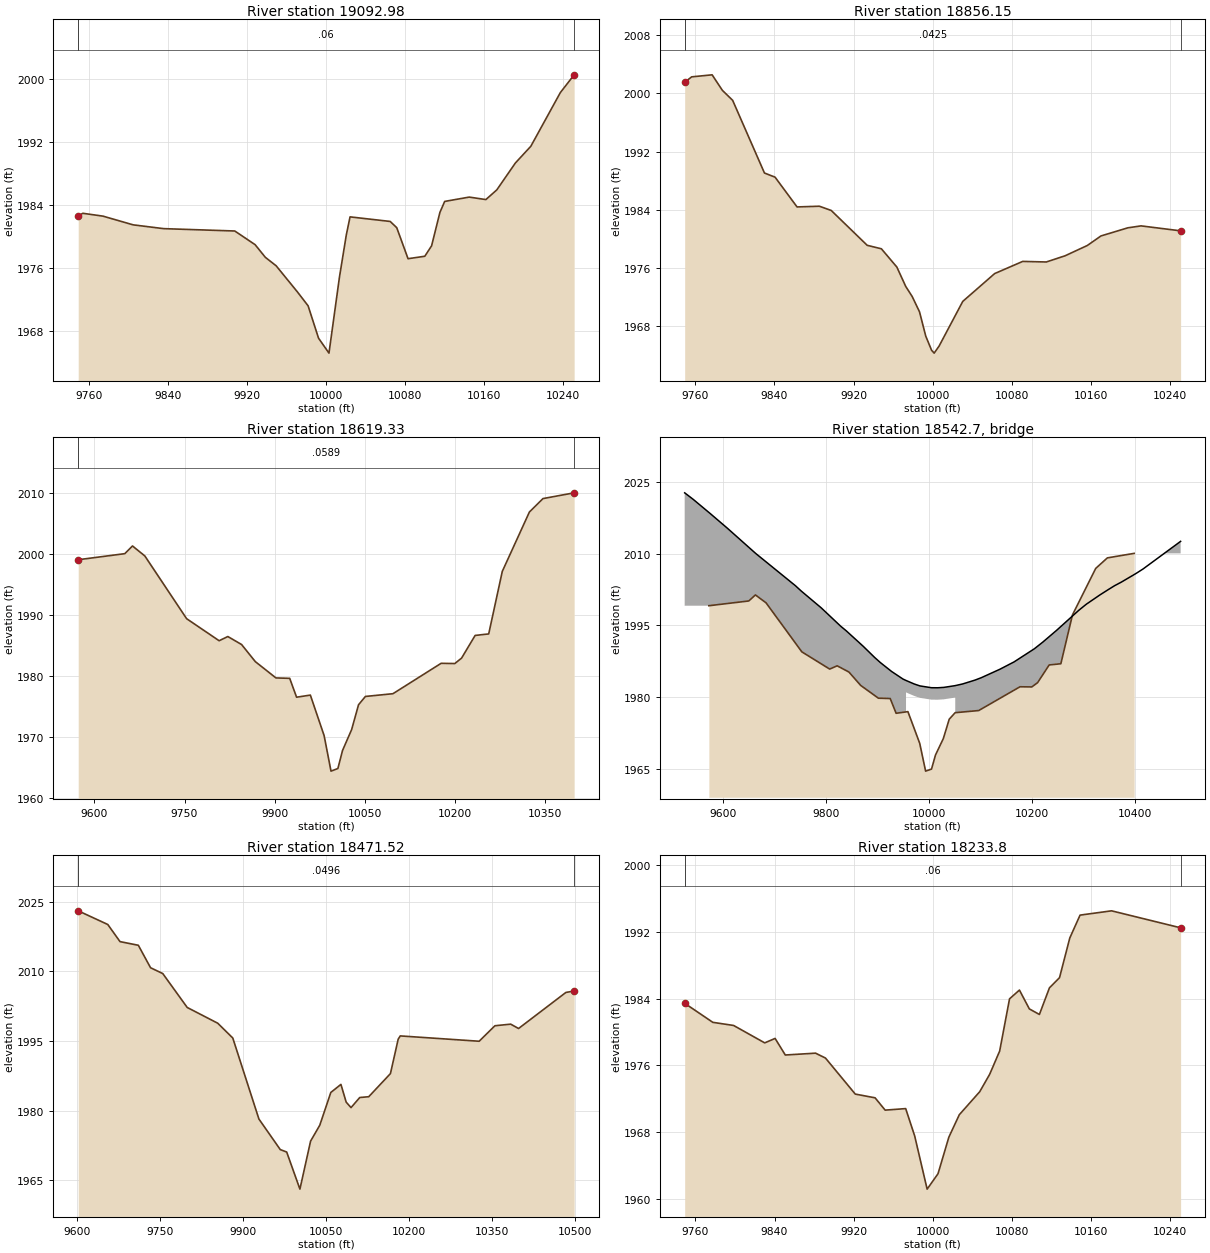
Type RM Length L Ch R = 1 ,19092.98,236.828000,236.828000,236.828000
XS GIS Cut Line= 6
711360.483928692761612.259891352711559.361521119761661.413146925
711594.579980547761743.208945411 711624.05702414761788.735222914
711675.164838612761842.872504333711736.108069641761891.564016239
#Sta/Elev= 30
9749.1071982.595 9753.711982.9539774.0961982.5949804.6741981.4849835.4741981.001
9907.5451980.7019928.1371978.9599938.4981977.347 9949.381976.2799970.9991972.939
9981.7381971.182 9992.291967.06910002.851965.16710013.431974.81610020.381980.197
10024.171982.497 10064.81981.91610071.431981.12110082.861977.17610099.82 1977.49
10106.671978.81410115.081983.05610119.911984.46210144.761985.01310161.611984.698
10172.671985.93210191.511989.358 10207.11991.47810236.971998.30910250.932000.565
#Mann= 3 , 0 , 0
9749.107    0.06       09749.107    0.06       010250.93    0.06       0
#XS Ineff= 2 , 0
       0                10041.61       0
Bank Sta=9749.107,10250.93
Exp/Cntr=0.3,0.1

Type RM Length L Ch R = 1 ,18856.15,236.828000,236.828000,236.828000
XS GIS Cut Line= 6
711158.181917606761690.071874686711250.660210424761720.642747522
711320.477541315761762.053793604711359.287769279761794.330250195
711460.451259038761897.202598353711554.889880246761983.933126321
#Sta/Elev= 30
9749.1262001.5379756.1892002.2859776.9072002.5659787.2662000.4289797.6741999.052
9829.8631989.0439840.5931988.4729862.8381984.3749885.4461984.4719897.4251983.887
9933.8291979.0879948.1931978.6099963.8331976.0959972.848 1973.429979.345 1972.04
9986.7511969.935 9993.091966.578    99991964.63210001.581964.24210006.551965.209
10030.541971.36610062.831975.19910091.221976.87210115.071976.79310134.081977.646
10156.581979.06510170.361980.37710197.571981.49710210.961981.76410250.981981.081
#Mann= 3 , 0 , 0
9749.126  0.0425       09749.126  0.0425       010250.98  0.0425       0
#XS Ineff= 2 , 0
       0                               0
Bank Sta=9749.126,10250.98
Exp/Cntr=0.3,0.1

Type RM Length L Ch R = 1 ,18619.33,147.802800,147.802800,147.802800
XS GIS Cut Line= 4
710907.212829858761811.148027316711186.037494421761965.895716161
711445.344432503 762110.88454175711630.948227871762208.250467188
#Sta/Elev= 30
9573.0461999.1269650.5742000.1229663.4122001.3859684.019 1999.749753.5061989.458
9807.6611985.8429822.1271986.5339845.0011985.2219867.8741982.4159902.2031979.743
9925.1171979.6749936.5741976.5829959.4881976.9289982.4021970.285 9993.861964.458
10005.321964.88610013.041967.83910028.231971.27710039.691975.33910051.141976.704
10096.971977.15510177.171982.13910199.93  1982.110211.221982.993 10233.81986.712
10256.39 1986.9610278.971997.20710324.142006.95410346.732009.15410398.622010.099
#Mann= 3 , 0 , 0
9573.046  0.0589       09573.046  0.0589       010398.62  0.0589       0
#XS Ineff= 2 , 0
       0                               0
Bank Sta=9573.046,10398.62
Exp/Cntr=0.3,0.1

Type RM Length L Ch R = 3 , 18542.7,,,
BEGIN DESCRIPTION:
END DESCRIPTION:
Bridge Culvert--1,0,-1,-1, 0
Deck Dist Width WeirC Skew NumUp NumDn MinLoCord MaxHiCord MaxSubmerge Is_Ogee
55.176400,37.450000,2.6,0, 41, 40, , , 0.95, 0, 0,0,,
 9526.10 9542.78 9576.31 9608.92 9664.03 9741.14 9752.12 9791.31 9829.02 9839.64
 9872.96 9894.92 9905.91 9927.88 9949.85 9955.79 9955.79 9971.82 9982.8010005.19
10017.2810029.3610051.3110051.3110065.6310089.8010101.8910138.1610165.6710204.88
10221.3210248.0310291.1710305.5510332.6410348.6910360.4710374.3910402.2110416.13
10488.91
 2022.79 2021.41 2018.39 2015.38 2010.08 2003.32 2002.23 1998.67 1994.83 1993.88
 1990.60 1988.28 1987.22 1985.34 1983.76 1983.46 1983.46 1982.72 1982.32 1981.94
 1981.93 1982.01 1982.38 1982.38 1982.73 1983.54 1984.04 1985.82 1987.36 1990.10
 1991.50 1993.96 1998.16 1999.42 2001.42 2002.52 2003.31 2004.11 2005.88 2006.84
 2012.62
 1022.79 1021.41 1018.39 1015.38 1010.08 1003.32 1002.23  998.67  994.83  993.88
  990.60  988.28  987.22  985.34  983.76  983.46 1980.96 1980.22 1979.82 1979.44
 1979.43 1979.51 1979.88  982.38  982.73  983.54  984.04  985.82  987.36  990.10
  991.50  993.96  998.16  999.42 1001.42 1002.52 1003.31 1004.11 1005.88 1006.84
 1012.62
 9526.10 9542.78 9576.31 9608.92 9664.03 9741.14 9752.12 9791.31 9829.02 9839.64
 9872.96 9894.92 9905.91 9927.88 9944.80 9944.80 9949.85 9960.83 9982.8010005.19
10017.2810029.3610040.3210040.3210060.0510089.8010113.4410161.7410204.8810221.32
10248.0310291.1710305.5510332.6410348.6910360.4710374.3910402.2110416.1310488.91
 2022.79 2021.41 2018.39 2015.38 2010.08 2003.32 2002.23 1998.67 1994.83 1993.88
 1990.60 1988.28 1987.22 1985.34 1984.12 1984.12 1983.76 1983.21 1982.32 1981.94
 1981.93 1982.01 1982.20 1982.20 1982.57 1983.54 1984.57 1987.09 1990.10 1991.50
 1993.96 1998.16 1999.42 2001.42 2002.52 2003.31 2004.11 2005.88 2006.84 2012.62
 1022.79 1021.41 1018.39 1015.38 1010.08 1003.32 1002.23  998.67  994.83  993.88
  990.60  988.28  987.22  985.34  984.12 1981.62 1981.26 1980.71 1979.82 1979.44
 1979.43 1979.51 1979.70  982.20  982.57  983.54  984.57  987.09  990.10  991.50
  993.96  998.16  999.42 1001.42 1002.52 1003.31 1004.11 1005.88 1006.84 1012.62
BR Coef=-1 , 0 , 0 ,, 0 ,,,0.8,0,1,0,
WSPro=,,,, 1 ,,,, 0 ,,,, 0 ,,,,-1 ,-1 ,-1 , 0 , 0 , 0 , 0 , 0
BC Design=,, 0 ,, 0 ,,,,,,

Type RM Length L Ch R = 1 ,18471.52,237.720700,237.720700,237.720700
XS GIS Cut Line= 4
710816.594813854761936.619126379 711120.51369825762078.819705337
711265.502523869762173.620091289711541.538941771762445.474139243
#Sta/Elev= 30
9601.6382023.0149655.0792020.074 9677.162016.3919710.2822015.6049732.3632010.771
9754.4442009.5169798.6052002.2259853.8081998.8319880.973 1995.659928.1651978.228
9966.7451971.6519978.382 1971.1210002.28 1963.1410021.561973.46910038.121976.875
10058.111983.93610076.381985.67310085.911981.84810094.661980.67910110.41 1982.85
10126.63 1983.0210165.851987.99410179.881995.40310183.631996.10310326.151994.955
10354.651998.28810383.151998.635 10397.41997.69710482.912005.45310497.842005.765
#Mann= 3 , 0 , 0
9601.638  0.0496       09601.638  0.0496       010497.84  0.0496       0
#XS Ineff= 2 , 0
       0                               0
Bank Sta=9601.638,10497.84
Exp/Cntr=0.3,0.1

Type RM Length L Ch R = 1 , 18233.8,286.396500,286.396500,286.396500
XS GIS Cut Line= 6
710867.838564174762275.777196653711026.450902928762315.275389596
711075.020409392762309.677669899711148.710110905762281.327710895
711203.160067632762279.083927967711349.506164909762328.149929918
#Sta/Elev= 30
9749.125 1983.439777.6341981.1419798.6261980.7689830.1141978.678 9840.611979.213
9850.9131977.2239881.5391977.4449891.5921976.8559921.7141972.5349941.7731972.086
9951.9631970.6079972.7261970.7939981.8161967.5179994.425 1961.1310005.441962.979
10016.391967.36110026.981970.05810047.631972.81810057.721974.912 10067.81977.695
 10077.81983.96410087.811985.01410097.841982.75410108.011982.08910118.171985.282
10128.361986.50110138.761991.26410149.151994.00810181.021994.52310250.881992.485
#Mann= 3 , 0 , 0
9749.125    0.06       09749.125    0.06       010250.88    0.06       0
#XS Ineff= 2 , 0
       0                               0
Bank Sta=9749.125,10250.88
Exp/Cntr=0.3,0.1

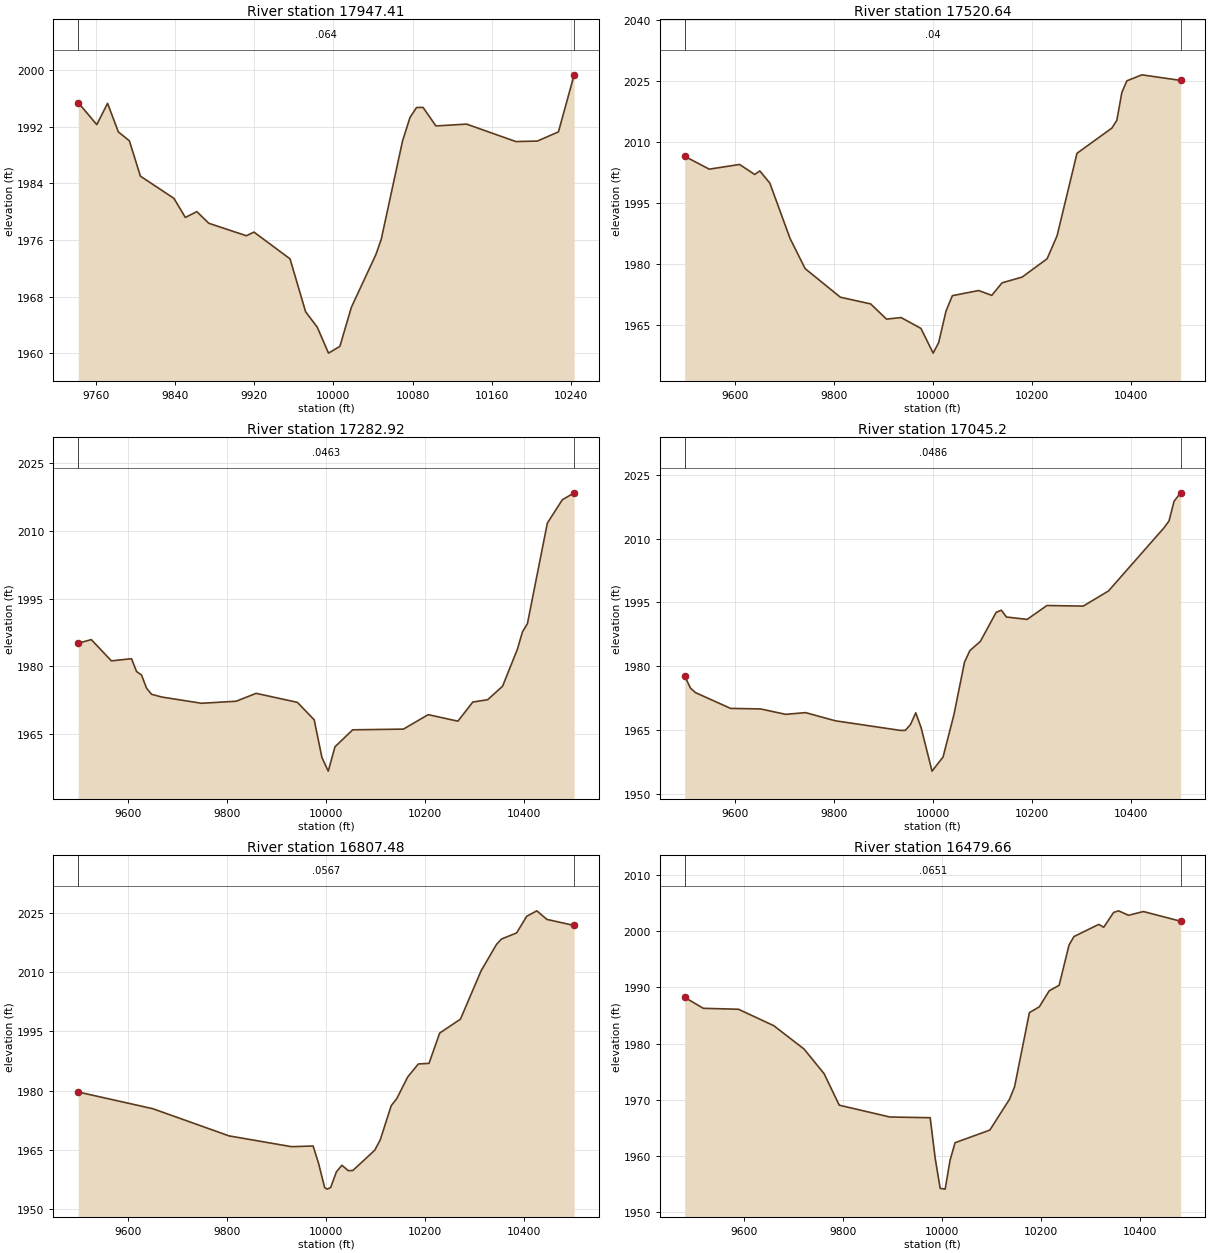
Type RM Length L Ch R = 1 ,17947.41,426.765500,426.765500,426.765500
XS GIS Cut Line= 6
710767.788553488762355.909824889710910.017533187762434.941816285
 710946.34142976762473.622855988710994.476455332762548.774051291
711039.288663563 762590.93646145 711159.87393434762649.095786062
#Sta/Elev= 30
9741.7331995.4179760.5271992.3019771.4461995.3129782.3651991.273 9793.511990.016
9804.6741985.0229838.5321981.8929850.1461979.1869861.7591980.0099873.8651978.362
9911.9061976.6019919.5981977.1179956.0771973.3349971.8521965.8539983.6591963.669
9994.9961960.01310006.491960.965 10018.11966.47810042.881973.92410048.321976.069
10069.89 1989.9810077.431993.30610084.121994.72210090.711994.73110103.661992.117
10134.711992.37610184.581989.90910206.311989.97910227.671991.27910243.561999.339
#Mann= 3 , 0 , 0
9741.733   0.064       09741.733   0.064       010243.56   0.064       0
#XS Ineff= 2 , 0
       0                               0
Bank Sta=9741.733,10243.56
Exp/Cntr=0.3,0.1

Type RM Length L Ch R = 1 ,17520.64,237.720600,237.720600,237.720600
XS GIS Cut Line= 6
710486.305610658762756.576999474710924.054694161762843.860761725
710951.169001938762858.157996651711010.472533364762916.272494565
711077.779305487 762944.18599316711442.428285158762992.691710541
#Sta/Elev= 30
9499.1422006.511 9548.822003.3519610.0322004.5089640.6222002.0429650.7982002.926
9671.1511999.9239711.8561986.3629742.3851978.9199813.6191971.8869874.6771970.247
9906.8021966.5069936.2591966.8889976.3541964.222   10001 1958.1510012.091960.724
 10026.91968.45610039.771972.26710092.851973.53110119.381972.34310140.151975.421
10180.771976.83910231.141981.33310251.261986.973 10291.52007.25210361.912013.437
10371.982015.35510382.092022.187 10392.2 2025.0510422.522026.52810500.792025.153
#Mann= 3 , 0 , 0
9499.142    0.04       09499.142    0.04       010500.79    0.04       0
#XS Ineff= 2 , 0
       0                               0
Bank Sta=9499.142,10500.79
Exp/Cntr=0.3,0.1

Type RM Length L Ch R = 1 ,17282.92,237.720700,237.720700,237.720700
XS GIS Cut Line= 6
 710378.98174628763073.380883741710720.703155301763116.165670939
710800.734390359 763100.27348351710897.625334768763031.436329004
710965.074462816763012.087621537711348.836390767763030.048776946
#Sta/Elev= 30
9499.1341985.1049525.5631985.9129566.1931981.1929606.8241981.6749616.9671978.834
9627.0761978.0419637.1851975.1229647.2941973.7799667.5121973.176 9748.18 1971.78
9818.3841972.2399858.4371973.9869941.8521971.9889975.7981968.1079991.3771959.751
10004.141956.72310017.75 1962.1310053.451965.89110155.971966.04610206.02 1969.26
10266.031967.80910296.07 1972.0510326.131972.57410356.191975.55410386.281983.806
10396.341987.615 10406.41989.44210446.642011.75110476.822016.938 10500.82018.485
#Mann= 3 , 0 , 0
9499.134  0.0463       09499.134  0.0463       0 10500.8  0.0463       0
#XS Ineff= 2 , 0
       0                               0
Bank Sta=9499.134,10500.8
Exp/Cntr=0.3,0.1

Type RM Length L Ch R = 1 , 17045.2,237.720700,237.720700,237.720700
XS GIS Cut Line= 6
710483.512946666763149.985759308710697.597253867763183.120056237
  710914.4203008763205.414378842711048.460648635763260.630501265
711143.888403137763291.740376091711457.993587214763360.229929393
#Sta/Elev= 30
9499.0991977.6779510.7431974.843 9520.881973.7739591.8381970.0579652.5321969.929
9703.0261968.6619743.318 1969.06 9803.651967.138  9934.41964.889  9944.91964.886
  9955.41966.2969965.8991969.0129976.6671965.5629998.7781955.30510021.081958.631
10042.861968.49910064.451980.95710075.251983.65410096.511985.82910128.251992.637
 10138.71993.15610149.16 1991.5510190.871990.986 10230.91994.25610304.171994.114
10355.22 1997.6710467.342012.52110477.532014.13810487.722018.76510500.962020.754
#Mann= 3 , 0 , 0
9499.099  0.0486       09499.099  0.0486       010500.96  0.0486       0
#XS Ineff= 2 , 0
       0                               0
Bank Sta=9499.099,10500.96
Exp/Cntr=0.3,0.1

Type RM Length L Ch R = 1 ,16807.48,327.821100,327.821100,327.821100
XS GIS Cut Line= 6
710326.875617074763251.209004236710674.319863516763327.751036729
710772.825914418763364.035316706711012.697830821763479.696001406
711116.574264093763510.433131279 711279.23122599 763542.09680267
#Sta/Elev= 30
9499.0591979.6839650.1971975.436 9803.821968.5699929.963 1965.849973.573 1966.01
9984.5881961.6329996.878 1955.4910002.021955.09410008.991955.49510020.631959.477
 10031.7 1961.1410044.751959.76510053.851959.81310098.13 1964.95 10109.2 1967.57
10131.351976.22510142.421977.97210164.531983.46310186.111986.77910207.681986.927
10229.191994.59210271.221998.13110312.842010.34210343.76    201710353.982018.404
10384.652019.953 10405.12024.17210425.512025.54610445.822023.37510500.88 2021.84
#Mann= 3 , 0 , 0
9499.059  0.0567       09499.059  0.0567       010500.88  0.0567       0
#XS Ineff= 2 , 0
       0                               0
Bank Sta=9499.059,10500.88
Exp/Cntr=0.3,0.1

Type RM Length L Ch R = 1 ,16479.66,623.061500,623.061500,623.061500
XS GIS Cut Line= 6
710258.049056392763609.577448209710712.639026227763698.172482306
710775.898169191763707.640297499710855.589347437763713.671002239
 711064.89541306763713.808859205711249.913845258763727.418037909
#Sta/Elev= 30
9480.7331988.2349518.3061986.2779589.4861986.1049660.6651983.1829721.6761979.033
9762.3931974.6269793.0481969.0059895.2311966.8999976.7091966.7749986.8151959.559
9996.8961954.18310006.981954.04210017.011959.24610027.04 1962.3210097.211964.566
10137.221970.10310147.221972.28610177.221985.51410197.221986.54310217.221989.399
10237.221990.37210257.221997.55310267.231999.06610317.262001.23510327.282000.723
10347.312003.36210357.332003.65210377.362002.85910407.462003.52510482.67  2001.8
#Mann= 3 , 0 , 0
9480.733  0.0651       09480.733  0.0651       010482.67  0.0651       0
#XS Ineff= 2 , 0
       0                               0
Bank Sta=9480.733,10482.67
Exp/Cntr=0.3,0.1