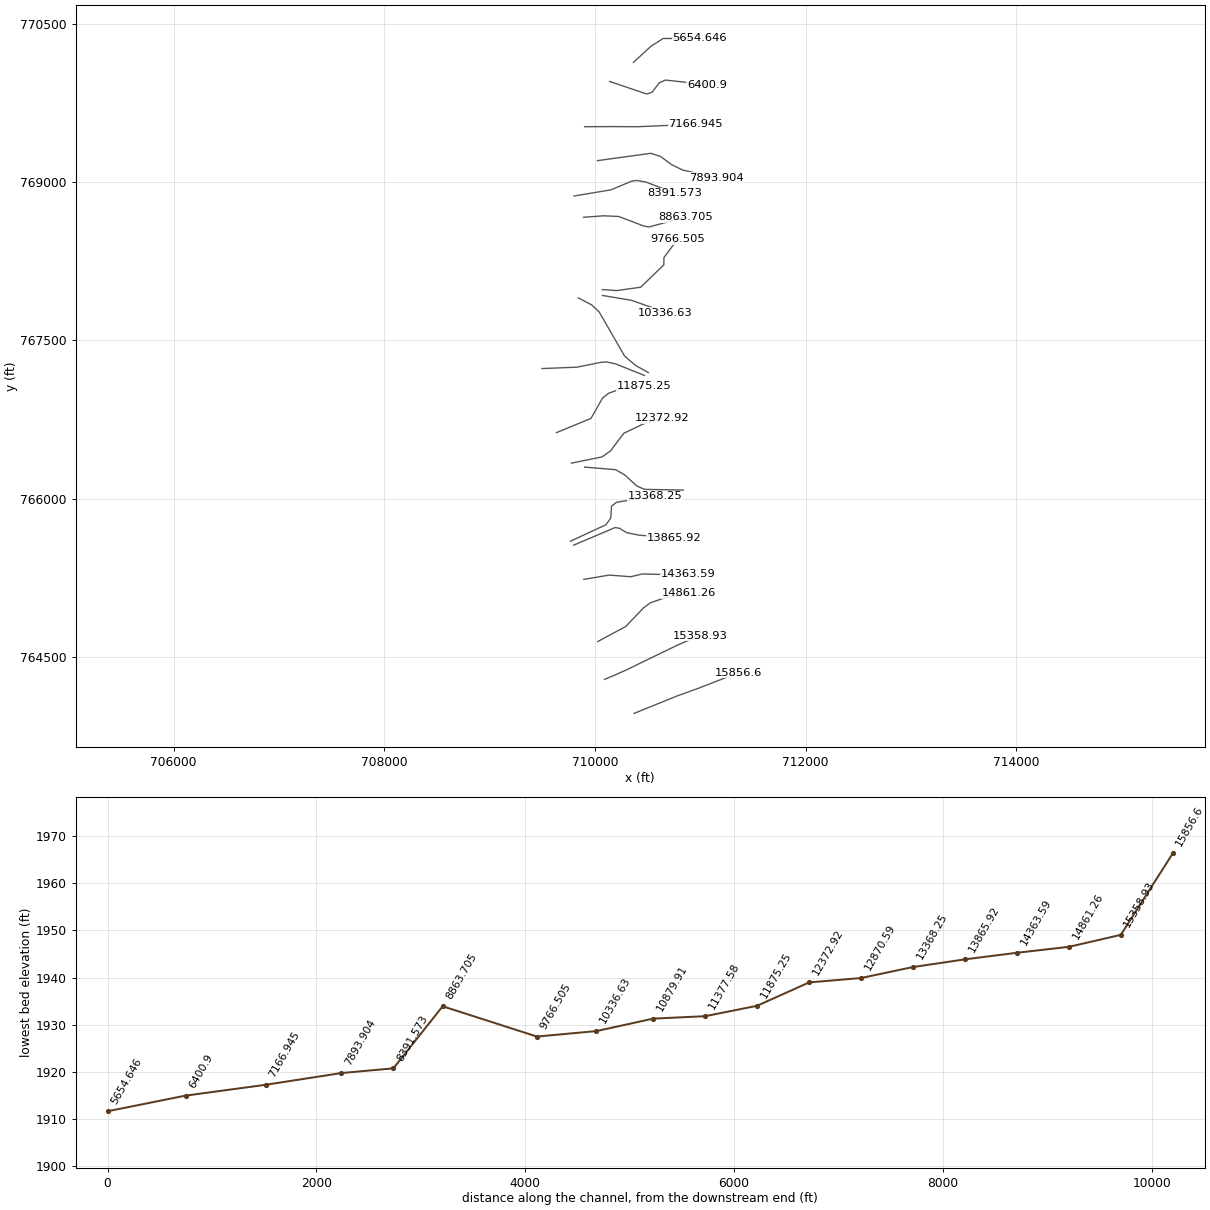
HEC-RAS study 14510_ras.prj: 14510

--- 14510_ras.g01 (geometry) --- (continued)

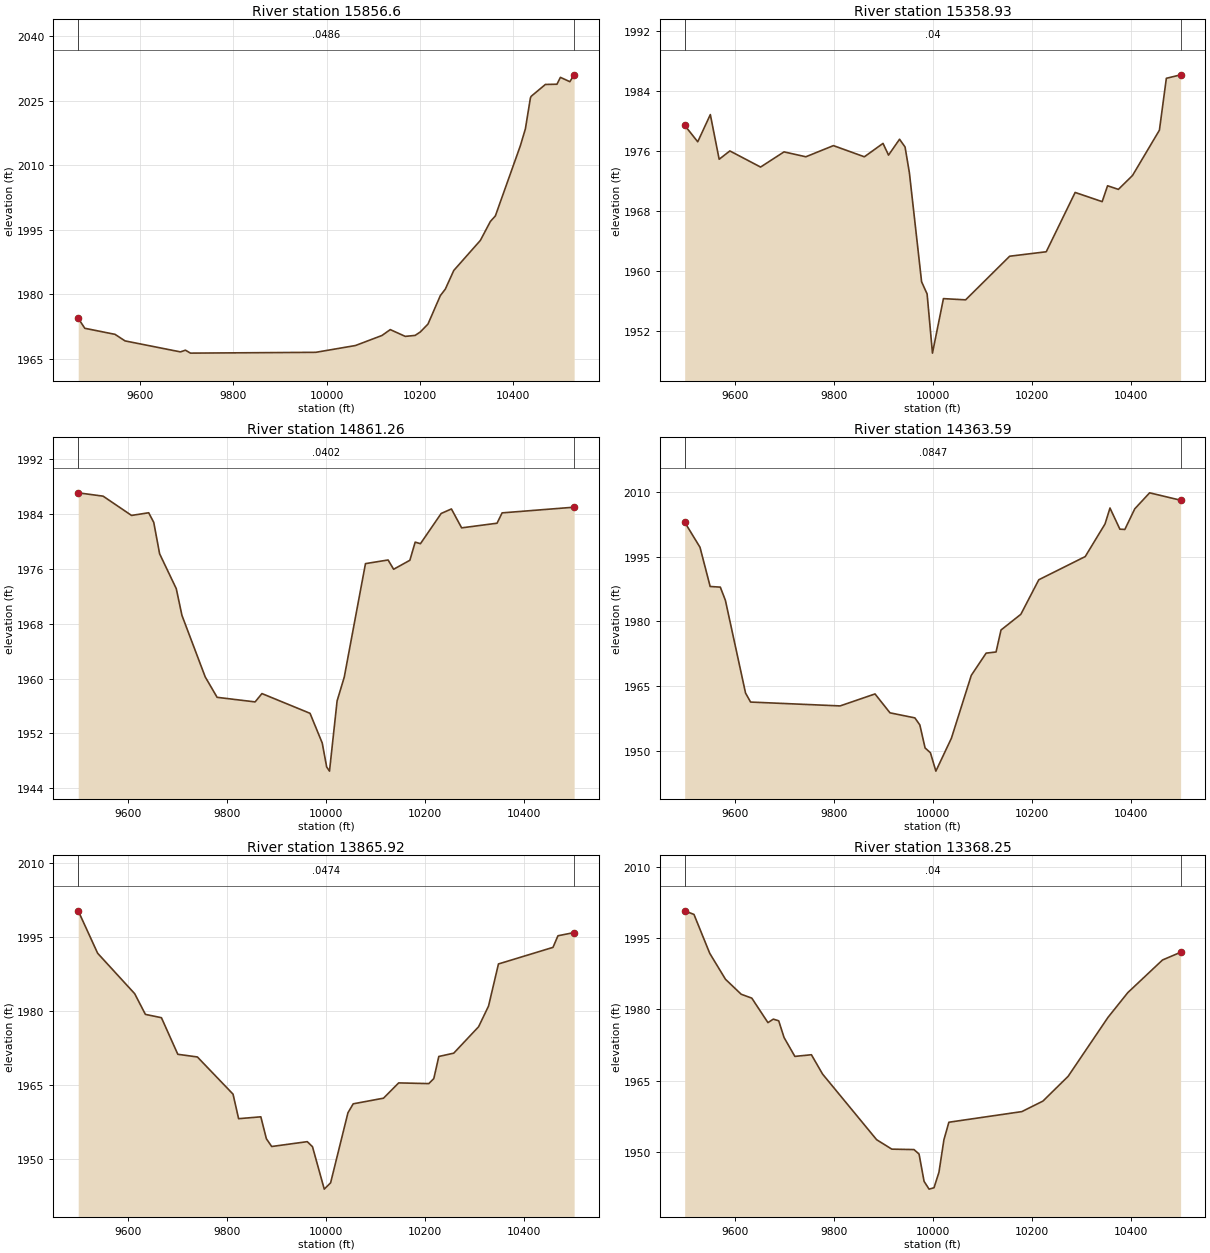
Type RM Length L Ch R = 1 , 15856.6,497.668200,497.668200,497.668200
XS GIS Cut Line= 4
710371.913842022763962.737499401710776.148913771 764126.15167734
  710978.2664496764199.258020088711362.433113545764348.337621018
#Sta/Elev= 30
9467.7661974.3949481.8811972.0629546.5981970.6549568.1711969.1279686.8191966.573
9697.6051966.9669708.3911966.2849976.9991966.47110062.071968.05210118.711970.382
10136.661971.75210168.841970.17710189.871970.40310201.021971.20510217.511973.042
10243.931979.64810254.661981.17210272.791985.50910329.74 1992.49 10351.21996.898
10361.921998.18910415.552014.52810426.28 2018.4410437.012025.60610438.642025.999
10469.192028.75910493.93 2028.8110501.372030.40810521.57  2029.410530.792030.997
#Mann= 3 , 0 , 0
9467.766  0.0486       09467.766  0.0486       010530.79  0.0486       0
#XS Ineff= 2 , 0
       0                               0
Bank Sta=9467.766,10530.79
Exp/Cntr=0.3,0.1

Type RM Length L Ch R = 1 ,15358.93,497.668300,497.668300,497.668300
XS GIS Cut Line= 6
710090.615144288764285.208857182710191.438043522764326.875943493
710298.543682606764374.958879311710778.714256367764607.667347919
 710891.87524264764657.231987035711001.795319883764700.780525656
#Sta/Elev= 30
9499.0251979.4579525.4111977.2589550.8431980.8959568.6921974.9269590.3321976.037
9652.3721973.8859699.7151975.9119743.8461975.2579799.5191976.7489862.0441975.256
9899.7311977.0459910.8651975.4819933.135  1977.69944.2691976.5639952.9961973.133
9977.6731958.5599988.7861956.9379999.6321949.03310021.791956.313 10066.61956.149
10155.571961.97510229.511962.57210287.891970.49410342.481969.265 10353.41971.387
10375.231970.90310403.831972.76110458.13 1978.8110472.151985.73910500.971986.203
#Mann= 3 , 0 , 0
9499.025    0.04       09499.025    0.04       010500.97    0.04       0
#XS Ineff= 2 , 0
       0                               0
Bank Sta=9499.025,10500.97
Exp/Cntr=0.3,0.1

Type RM Length L Ch R = 1 ,14861.26,497.668200,497.668200,497.668200
XS GIS Cut Line= 6
710027.291690282764643.962909715710291.966920887764786.159143771
710461.047519904 764962.85902817710526.825684803765011.344984479
710660.945906802765057.860259025710888.309473358765100.794324611
#Sta/Elev= 30
 9499.091987.0959549.3851986.6099606.8051983.7989641.4711984.1869651.6781982.787
9663.535  1978.29697.1571973.1179708.6661969.2119755.6171960.2479779.6691957.264
 9856.421956.5969870.2321957.8119967.3761954.9319991.9961950.604   100011947.103
10006.681946.49810022.071956.74710036.511960.21210079.361976.76610125.021977.299
10136.251975.94510169.031977.25510179.771979.90310190.411979.67410232.281984.084
10252.971984.74310273.611981.98510345.131982.66210355.35 1984.1710500.891985.001
#Mann= 3 , 0 , 0
 9499.09  0.0402       0 9499.09  0.0402       010500.89  0.0402       0
#XS Ineff= 2 , 0
       0                               0
Bank Sta=9499.09,10500.89
Exp/Cntr=0.3,0.1

Type RM Length L Ch R = 1 ,14363.59,497.668200,497.668200,497.668200
XS GIS Cut Line= 6
709894.839467936765233.669587199710134.206072528765274.152598005
710341.070396793765258.733005237710450.948110054 765285.28318847
710690.017540828765278.245000431710887.568522001765283.997764305
#Sta/Elev= 30
9499.1932003.068 9530.141997.2339550.6611988.1259571.1831987.9749581.4431984.908
9622.1581963.3679632.3351961.283 9813.151960.3869883.6511963.1689913.9031958.781
9964.1421957.6069974.2361955.9589984.7661950.6259995.5821949.50510006.571945.241
10037.911952.877 10078.11967.48410108.111972.64710128.131972.91110138.141978.016
10178.191981.66410214.481989.68910308.241995.07210348.25 2002.6510358.252006.351
10378.252001.43110388.25 2001.3710408.272006.15610438.292009.87710500.912008.158
#Mann= 3 , 0 , 0
9499.193  0.0847       09499.193  0.0847       010500.91  0.0847       0
#XS Ineff= 2 , 0
       0                               0
Bank Sta=9499.193,10500.91
Exp/Cntr=0.3,0.1

Type RM Length L Ch R = 1 ,13865.92,497.668300,497.668300,497.668300
XS GIS Cut Line= 6
709798.063044797765557.881415115 710192.16376547765725.222440268
710234.408383066765717.874533812710300.411856483765676.792285823
710417.178522117765653.059049022710747.701491422765627.327930681
#Sta/Elev= 30
9499.235 2000.249538.4541991.6479613.3531983.4429634.9391979.2579667.3181978.582
9700.3961971.1679739.9251970.6289811.9471963.0899823.1681958.1219868.0531958.497
9879.2741954.0559890.0011952.4829961.8631953.4669972.4071952.4369996.1521943.846
10008.981945.12410043.981959.31110054.61 1961.1310115.841962.27510146.451965.371
10207.29 1965.23 10217.41966.248 10227.51970.72510257.671971.39710307.891976.756
10327.931980.94410347.971989.47210458.111992.83510468.111995.18610500.841995.838
#Mann= 3 , 0 , 0
9499.235  0.0474       09499.235  0.0474       010500.84  0.0474       0
#XS Ineff= 2 , 0
       0                               0
Bank Sta=9499.235,10500.84
Exp/Cntr=0.3,0.1

Type RM Length L Ch R = 1 ,13368.25,497.668200,497.668200,497.668200
XS GIS Cut Line= 6
709767.273974583765595.157402197710104.532317566765751.506918028
 710150.54402295 765814.97750323  710157.8854039765928.130357498
710205.980463849765965.121575237710571.490821724766022.682470586
#Sta/Elev= 30
9499.208  2000.79517.9951999.9439549.7921991.7789581.5881986.3219613.3851983.168
9634.7611982.3559667.3691977.2079678.2391977.9429689.1081977.5889699.9771974.061
9721.716 1970.119755.1621970.4589777.6971966.396 9886.861952.6029917.538 1950.62
9962.368 1950.539972.5271949.5919982.6851943.852 9992.721942.21910002.72 1942.51
10012.731945.76710022.741952.59410032.751956.27510180.051958.50810222.681960.718
10273.561965.91910354.041978.30310394.111983.51310464.211990.37310500.75 1991.99
#Mann= 3 , 0 , 0
9499.208    0.04       09499.208    0.04       010500.75    0.04       0
#XS Ineff= 2 , 0
       0                               0
Bank Sta=9499.208,10500.75
Exp/Cntr=0.3,0.1

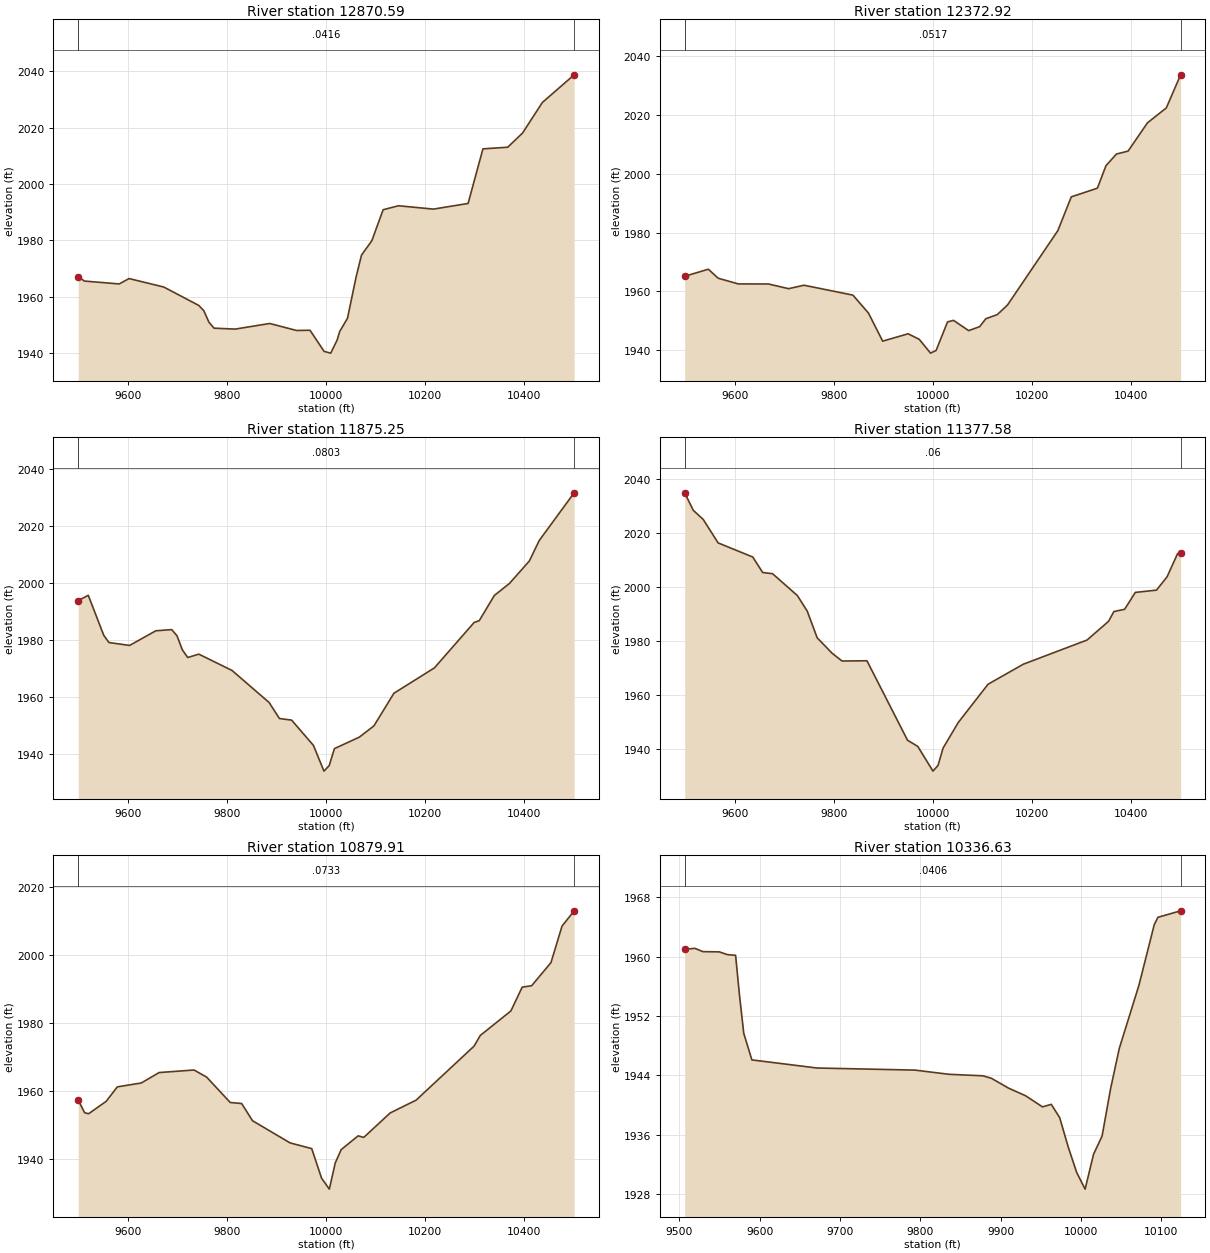
Type RM Length L Ch R = 1 ,12870.59,497.668200,497.668200,497.668200
XS GIS Cut Line= 6
709902.271217758766298.503936526710194.850221194766274.144153799
710281.571179822766225.744802315710398.848622902766118.743950723
710472.032150435 766087.18726943710839.136199968766080.528092027
#Sta/Elev= 30
9499.2231967.0049511.9531965.5039581.9611964.4829601.9721966.3989672.0441963.385
9742.6941956.8489752.8081955.0029763.2031950.8889773.6171948.7649816.1761948.435
9886.007 1950.439940.0811947.9489967.3831948.0169995.8321940.50710009.171939.894
10022.081944.51410027.18 1947.5410042.991952.25310060.631967.09910071.321974.727
10092.191979.84210115.031990.85610146.051992.27610216.561991.084 10286.61993.092
 10316.62012.49910366.612013.07910396.62 2018.1310436.632028.99210500.79 2038.81
#Mann= 3 , 0 , 0
9499.223  0.0416       09499.223  0.0416       010500.79  0.0416       0
#XS Ineff= 2 , 0
       0                               0
Bank Sta=9499.223,10500.79
Exp/Cntr=0.3,0.1

Type RM Length L Ch R = 1 ,12372.92,497.668300,497.668300,497.668300
XS GIS Cut Line= 6
709777.678513118766336.044275493710068.681305161 766395.26540179
710148.098977951766452.214515135710273.775255142766618.655944172
 710462.11449427766708.941635755710639.929394975 766761.93304753
#Sta/Elev= 30
9499.1191965.1099546.8631967.5149567.0421964.434  9607.41962.5159668.207 1962.49
9709.1331960.8939740.0931962.0699838.9851958.6989870.4081952.5789899.0321943.033
9950.3771945.5399972.9171943.655 9995.671938.95810006.92 1939.8510030.071949.576
10042.021950.11710072.741946.61510094.921947.96810107.441950.67110130.531952.064
10151.151955.32210252.871980.63710280.011992.14110332.71 1995.0910350.132002.767
 10371.32006.72110394.732007.71210433.952017.34510471.942022.41110500.842033.673
#Mann= 3 , 0 , 0
9499.119  0.0517       09499.119  0.0517       010500.84  0.0517       0
#XS Ineff= 2 , 0
       09841.678                       0
Bank Sta=9499.119,10500.84
Exp/Cntr=0.3,0.1

Type RM Length L Ch R = 1 ,11875.25,497.668200,497.668200,497.668200
XS GIS Cut Line= 6
 709635.54584681766625.316301438709962.368788934766759.879921259
710072.163281222  766952.3454494 710130.17029745  766998.8321384
710281.929842462 767052.79903289710465.482510123767065.853654867
#Sta/Elev= 30
9499.1641993.7439519.4561995.6539550.7471981.6369561.1781979.096  9602.91978.071
9656.011 1983.219687.983 1983.629698.6411981.4739709.4791976.5429720.3691973.843
9742.8691975.0139809.8771969.297 9884.661958.0869905.5971952.4569930.2051951.899
9974.3361943.0179995.4891934.01410006.071935.92610016.641941.90110066.941945.925
10096.521949.885 10136.81961.30610218.581970.19510298.891986.12410309.211986.752
10339.741995.59710370.141999.78710410.342007.65910430.362014.85110500.862031.561
#Mann= 3 , 0 , 0
9499.164  0.0803       09499.164  0.0803       010500.86  0.0803       0
#XS Ineff= 2 , 0
       0                               0
Bank Sta=9499.164,10500.86
Exp/Cntr=0.3,0.1

Type RM Length L Ch R = 1 ,11377.58,497.668200,497.668200,497.668200
XS GIS Cut Line= 6
709497.503011217767232.908710587709831.638968353767246.133675126
710053.599680982767291.458479817710109.626236258767295.621341085
710196.637007122767277.364654913710470.694910312767167.966034697
#Sta/Elev= 30
9499.0822034.9169516.585 2028.419536.5932025.0479566.6052016.3699636.632 2011.13
9656.6392005.4039676.6472004.9459726.667 1996.879746.7051991.0789766.7481981.201
9796.8121975.5079816.8551972.6129867.2811972.6949949.2731943.2499969.9721940.967
10000.661931.81110010.841933.93410021.021940.33310051.561949.78410111.951964.015
10183.271971.43210311.811980.37410355.221987.28710366.081990.92710387.781991.766
10409.321998.02110452.051998.87110473.422003.76210494.792012.40310500.872012.656
#Mann= 3 , 0 , 0
9499.082    0.06       09499.082    0.06       010500.87    0.06       0
#XS Ineff= 2 , 0
       0                               0
Bank Sta=9499.082,10500.87
Exp/Cntr=0.3,0.1

Type RM Length L Ch R = 1 ,10879.91,543.286700,543.286700,543.286700
XS GIS Cut Line= 6
709843.166159965767903.165469923709967.930233679767837.622795837
710040.533686899767770.029520428710282.144717537 767350.92946561
710385.170425816767262.961492636710506.886911034767195.419538498
#Sta/Elev= 30
9499.172 1957.519512.0281953.7469520.0721953.4339555.7091957.0819578.1431961.325
9626.5341962.468 9662.561965.5339733.0481966.283 9758.541964.2059806.2611956.739
9829.307 1956.449851.2981951.3859927.1091944.8769970.8321943.1949990.5811934.563
10006.381931.29710018.371938.99110030.361942.906 10064.61946.94310075.991946.489
10129.241953.66710181.64 1957.4310298.761973.29610311.351976.443 10373.11983.625
10395.951990.61310415.091991.04310454.061997.81110476.422008.547 10500.92013.034
#Mann= 3 , 0 , 0
9499.172  0.0733       09499.172  0.0733       0 10500.9  0.0733       0
#XS Ineff= 2 , 0
       0                               0
Bank Sta=9499.172,10500.9
Exp/Cntr=0.3,0.1

Type RM Length L Ch R = 1 ,10336.63,570.121800,570.121800,570.121800
XS GIS Cut Line= 6
710072.507679343767926.317666888710348.967611939767879.740178227
710500.896879754767826.209384259710582.671579852767798.935271154
710622.418683999767783.130096295710664.545766297767762.654727711
#Sta/Elev= 30
9506.6191960.9889519.287 1961.139529.428 1960.68 9549.711960.6519559.8511960.276
9569.9921960.1879574.7421954.9199580.1331949.6829590.2741946.0829671.401 1944.99
9793.3491944.7079835.6161944.1419877.8821943.9389888.4481943.6039909.6251942.282
9931.0511941.2439951.9771939.7479962.9181940.0929973.4371938.2839983.9571934.359
9994.4771930.92510005.011928.65810015.591933.37910026.171935.81510036.791942.228
10047.551947.622   100721956.14110091.051964.30710095.661965.313 10123.91966.185
#Mann= 3 , 0 , 0
9506.619  0.0406       09506.619  0.0406       0 10123.9  0.0406       0
#XS Ineff= 2 , 0
       0                               0
Bank Sta=9506.619,10123.9
Exp/Cntr=0.3,0.1

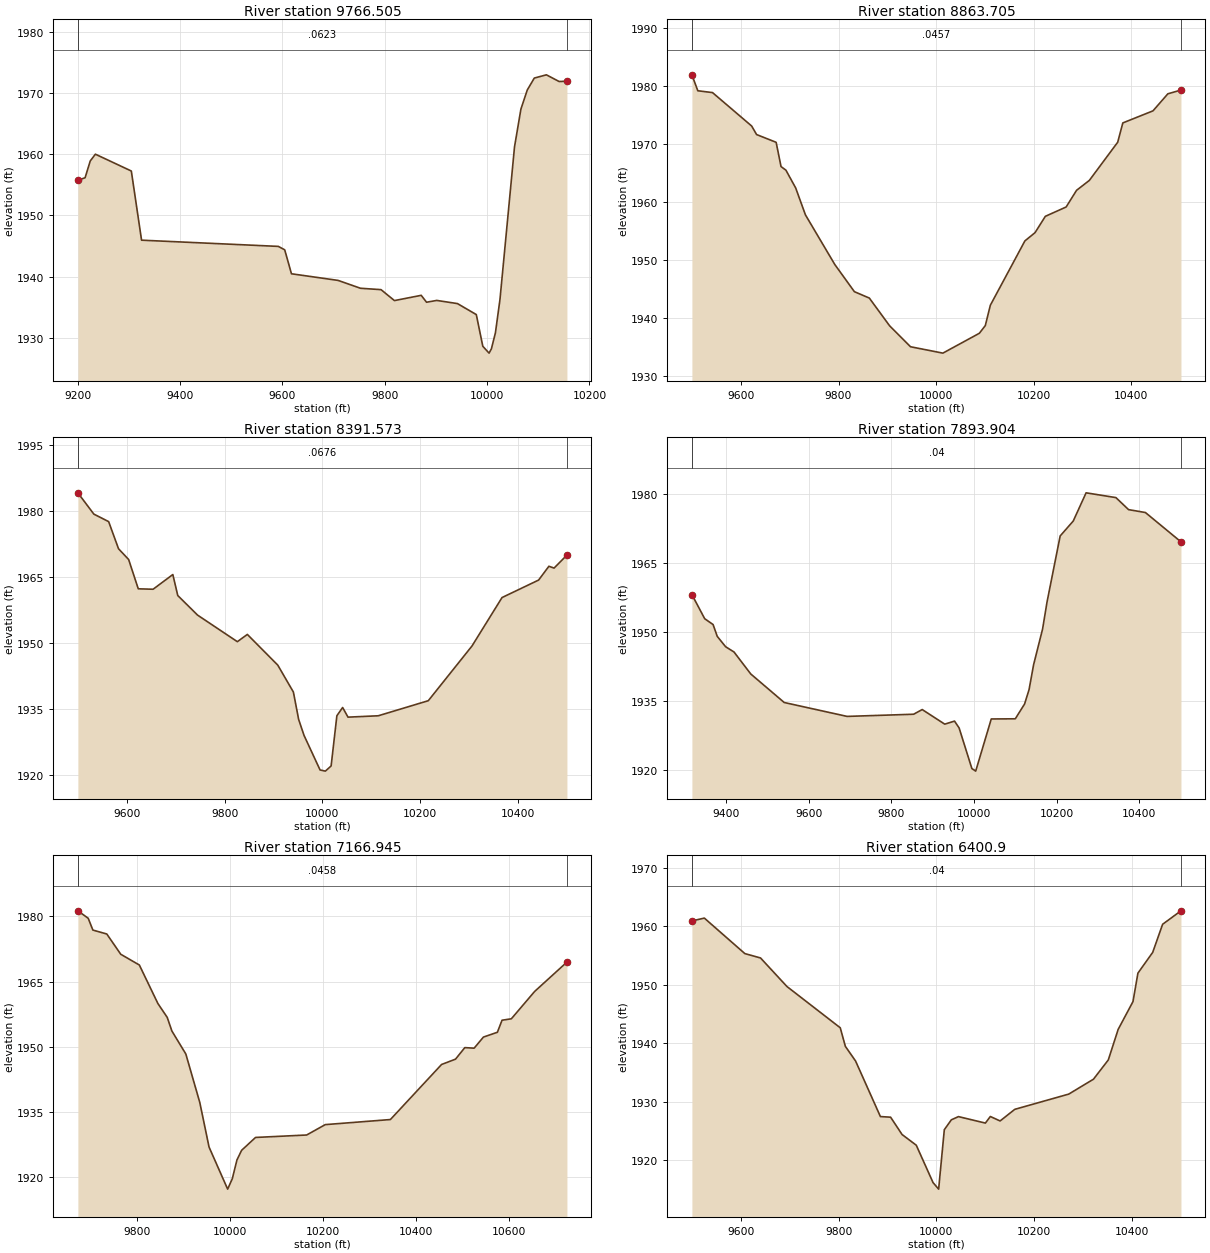
Type RM Length L Ch R = 1 ,9766.505,902.800300,902.800300,902.800300
XS GIS Cut Line= 6
710070.955613083767981.997384134710206.438810091767972.601350469
710434.610091001 768004.44764784710653.975037545768216.300096184
710655.477537155 768285.41507934710782.996938161768457.230693298
#Sta/Elev= 30
 9200.151955.7279214.2811956.1339224.3431958.8789234.4051959.9839304.6541957.233
9324.658 1945.949591.9951944.9259604.4691944.3669617.6651940.4549708.847 1939.37
9752.5921938.0889792.7581937.8629818.9351936.0769871.2891936.9359881.6931935.808
9901.6971936.1029942.1221935.5859978.9651933.7919991.6581928.62110003.871927.496
10008.441928.18910016.32 1930.8110025.221936.26310053.681961.19910066.141967.341
10078.591970.46410092.331972.41310115.951972.94310140.86 1971.8510156.091971.903
#Mann= 3 , 0 , 0
 9200.15  0.0623       0 9200.15  0.0623       010156.09  0.0623       0
#XS Ineff= 2 , 0
       0                               0
Bank Sta=9200.15,10156.09
Exp/Cntr=0.3,0.1

Type RM Length L Ch R = 1 ,8863.705,472.132400,472.132400,472.132400
XS GIS Cut Line= 6
709892.927451483768668.032820392710085.358790114768681.624085657
710225.360049388 768675.56551629710463.123654582768584.892983516
710515.172564763768575.963643626710861.391507039768670.505260765
#Sta/Elev= 30
9499.6891981.9199511.8071979.171 9541.921978.8549622.1611973.0839632.1751971.617
9672.2351970.279 9682.251966.0959692.2651965.4729712.2661962.4079732.2661957.758
9792.3591949.2069832.5321944.5139863.1491943.4099904.6511938.6319947.4921935.015
10013.761933.91510088.441937.33610100.681938.66610110.991942.17510181.781953.274
10202.491954.69210223.671957.51310266.261959.12310287.561961.99610313.731963.703
10371.881970.29510382.331973.62210444.121975.70310474.611978.64510501.431979.292
#Mann= 3 , 0 , 0
9499.689  0.0457       09499.689  0.0457       010501.43  0.0457       0
#XS Ineff= 2 , 0
       0                               0
Bank Sta=9499.689,10501.43
Exp/Cntr=0.3,0.1

Type RM Length L Ch R = 1 ,8391.573,497.668200,497.668200,497.668200
XS GIS Cut Line= 6
709802.664566007768869.449733507710152.604175845768928.109805161
710347.547325864769009.536935716710397.081606003769017.515050091
710488.760126683769000.454374992710759.894159853768896.192323853
#Sta/Elev= 30
9499.064 1984.049531.7671979.2059562.1081977.4949582.3351971.328 9603.081968.879
 9622.791962.2179653.131 1962.129693.5861965.4639703.6991960.6899744.1891956.246
 9825.731950.1989846.2131951.8489908.5691944.8669940.5591938.7419951.2961932.517
9962.2561928.9139995.1391921.035   100061920.768 10017.8 1921.94 10029.61933.362
10041.391935.23510052.411933.04110114.441933.35110216.87 1936.7810306.451949.231
10367.891960.23210442.751964.202 10463.91967.34410474.481966.93110500.81 1969.88
#Mann= 3 , 0 , 0
9499.064  0.0676       09499.064  0.0676       010500.81  0.0676       0
#XS Ineff= 2 , 0
       0                               0
Bank Sta=9499.064,10500.81
Exp/Cntr=0.3,0.1

Type RM Length L Ch R = 1 ,7893.904,726.959200,726.959200,726.959200
XS GIS Cut Line= 6
710024.427691042769204.944855139710531.227985322769274.416195601
710623.309440732769244.606873304710729.692460328769166.108986363
710830.834636986769116.638819769711149.939995676769041.590196639
#Sta/Elev= 30
9317.3671958.1729348.3351952.9179368.5941951.6539378.7241949.0769398.9831946.819
9419.2421945.683 9459.761940.9059540.7971934.6939693.058 1931.679853.9241932.143
9874.7151933.1629929.2531929.9869952.896 1930.659964.0171929.1629994.9081920.331
10004.15 1919.7710041.851931.11310099.991931.15110122.461934.37310133.361937.523
10144.26  1942.910166.071950.69210176.841956.58110208.591970.91610240.251974.165
10271.311980.29610343.481979.25710374.13 1976.6410414.851976.013 10500.91969.637
#Mann= 3 , 0 , 0
9317.367    0.04       09317.367    0.04       0 10500.9    0.04       0
#XS Ineff= 2 , 0
       0                               0
Bank Sta=9317.367,10500.9
Exp/Cntr=0.3,0.1

Type RM Length L Ch R = 1 ,7166.945,766.045500,766.045500,766.045500
XS GIS Cut Line= 4
 709902.72522074769526.479776725710158.150158435769527.982276365
 710406.06259799769526.479776725710954.474964261769550.519770876
#Sta/Elev= 30
9672.8071981.2839695.0821979.5729705.0821976.8599735.0831975.9519765.0831971.295
9805.0841968.8219845.0841959.9529865.085 1956.789875.0851953.6489905.0861948.364
9935.0861937.2399955.0861926.9519995.087 1917.2810005.091919.67510015.091923.985
10025.091926.20110055.091929.16410165.091929.72710205.121932.11510345.251933.282
10455.361945.94410485.391947.17310505.411949.82410525.431949.69510545.441952.247
10575.471953.35310585.481956.125 10605.51956.45210655.551962.73110725.091969.491
#Mann= 3 , 0 , 0
9672.807  0.0458       09672.807  0.0458       010725.09  0.0458       0
#XS Ineff= 2 , 0
       0                               0
Bank Sta=9672.807,10725.09
Exp/Cntr=0.3,0.1

Type RM Length L Ch R = 1 ,  6400.9,746.253500,746.253500,746.253500
XS GIS Cut Line= 6
 710140.12128485769955.927311953710491.696967298769836.904550282
710543.180765699769853.897379696710612.083287957769944.223317555
710670.182932142769969.098572366  711062.1594269769926.406445516
#Sta/Elev= 30
9499.2961960.9339524.7691961.4239607.7051955.3429639.8361954.5929693.9131949.702
 9803.061942.6349813.5531939.4529834.5381936.926 9885.331927.4189906.1831927.315
9929.729 1924.349958.7571922.513  9993.11916.11210004.561914.98910016.171925.166
10030.591926.86410045.151927.41210100.291926.304 10110.41927.43210130.431926.668
10160.471928.65810271.071931.27210321.631933.82310351.97 1937.1210372.191942.353
10402.531947.11710412.641951.98910442.981955.558 10463.21960.36210500.781962.668
#Mann= 3 , 0 , 0
9499.296    0.04       09499.296    0.04       010500.78    0.04       0
#XS Ineff= 2 , 0
       0                               0
Bank Sta=9499.296,10500.78
Exp/Cntr=0.3,0.1

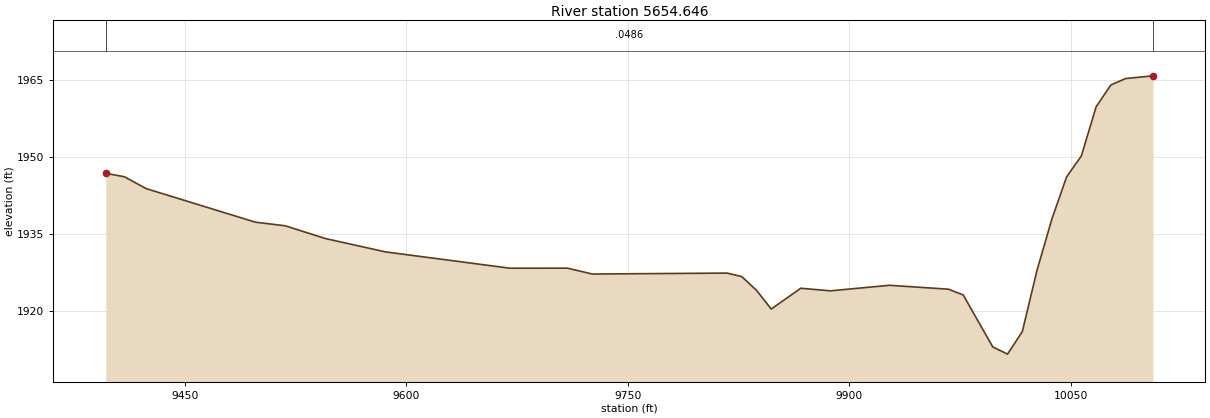
Type RM Length L Ch R = 1 ,5654.646,746.751200,746.751200,746.751200
XS GIS Cut Line= 4
710365.495107859770136.494627982710532.604038775770289.875951573
710647.965038985770363.372072682710993.539954722770364.874572322
#Sta/Elev= 30
9396.3781946.8239408.9561946.1549423.7441943.8469497.6871937.3249517.8691936.625
9545.0161934.1499585.7371931.5539669.9651928.3819709.046 1928.399725.7981927.248
9817.026 1927.439827.0261926.7539837.0261924.0949847.0261920.4449867.0261924.487
9887.026 1923.989927.0271925.0589967.0271924.3039977.0271923.1819997.0271913.087
10007.031911.68410017.031916.05710027.031928.00610037.031937.90910047.031946.125
10057.031950.19810067.031959.75410077.031963.99110087.031965.23710105.571965.765
#Mann= 3 , 0 , 0
9396.378  0.0486       09396.378  0.0486       010105.57  0.0486       0
#XS Ineff= 2 , 0
       0                               0
Bank Sta=9396.378,10105.57
Exp/Cntr=0.3,0.1