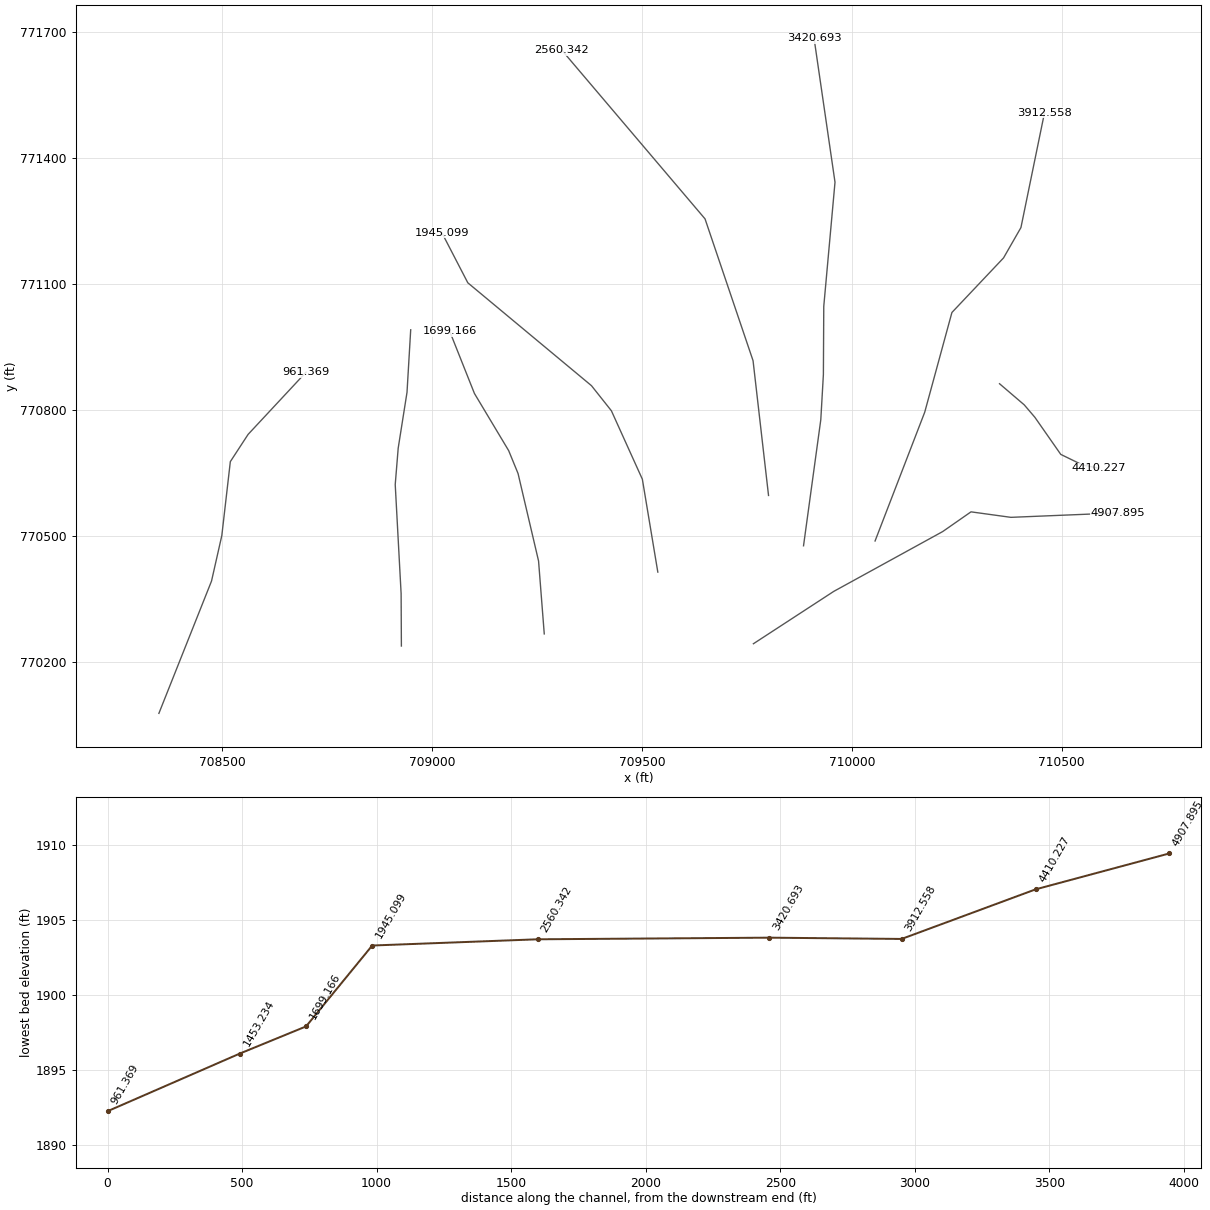
HEC-RAS study 14510_ras.prj: 14510

--- 14510_ras.g01 (geometry) --- (continued)

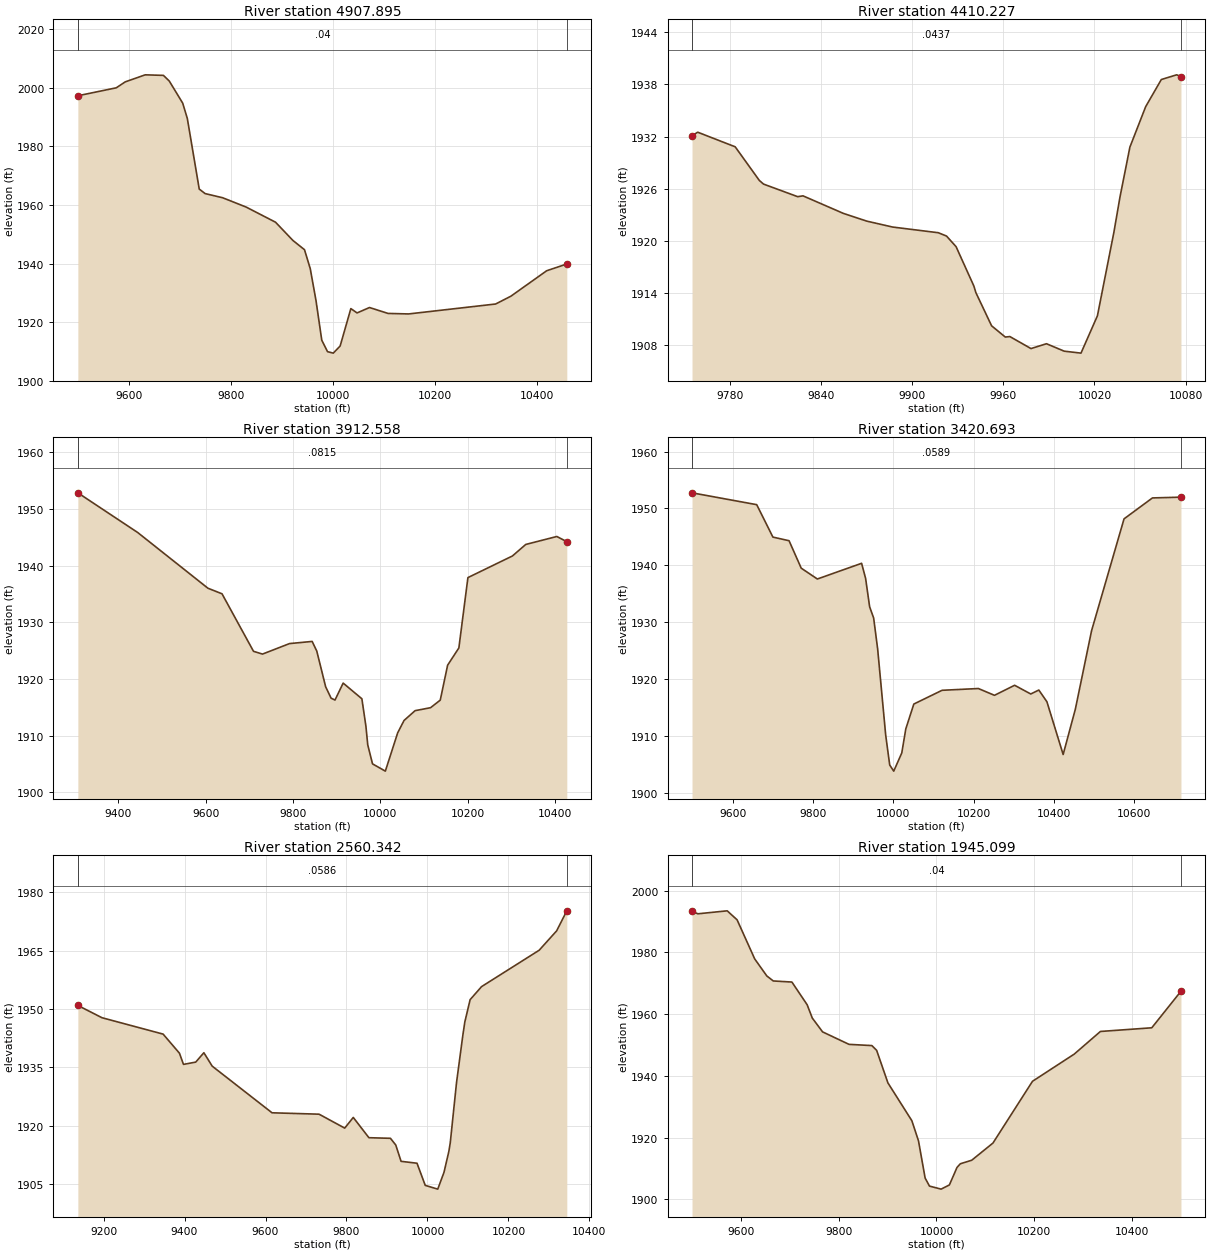
Type RM Length L Ch R = 1 ,4907.895,497.668300,497.668300,497.668300
XS GIS Cut Line= 6
709765.341175686770242.440109427709956.868928358770367.226727805
710216.437503424770509.774012325710283.881188788770556.757051239
710379.017604589770543.672028705710634.442542315770554.189526156
#Sta/Elev= 30
9499.0391997.2279574.3181999.9389592.0062001.9749631.1542004.3699666.8532004.177
9678.317 2002.249704.604 1994.719713.6891989.472 9737.041965.4039748.5491963.866
9783.0731962.4399829.1061959.2589886.6481954.1039920.7991947.8669943.389 1944.73
9954.6831938.2899965.978 1927.389977.2731913.8659988.567 1909.959999.8451909.453
10013.321911.88710034.311924.64110046.491923.16210070.871925.008 10107.21922.995
10147.571922.81810318.181926.204 10348.2 1928.8810418.261937.54610457.741939.849
#Mann= 3 , 0 , 0
9499.039    0.04       09499.039    0.04       010457.74    0.04       0
#XS Ineff= 2 , 0
       0                               0
Bank Sta=9499.039,10457.74
Exp/Cntr=0.3,0.1

Type RM Length L Ch R = 1 ,4410.227,497.668200,497.668200,497.668200
XS GIS Cut Line= 6
710351.897130679770862.090247098710410.812136287770811.717645045
710436.113821559 770782.09652611710497.856519853770693.671837069
710548.698941007770668.957925757710587.839521009770660.636634014
#Sta/Elev= 30
9755.2941932.0989759.0391932.5049783.6811930.8239799.5721926.9479802.3421926.527
9824.7971925.0789828.3051925.1729854.9581923.1459870.2141922.2639887.1861921.581
9917.2961920.9259922.6971920.541 9928.981919.3219940.6651914.7939942.0311914.018
9952.3491910.2039961.3641908.9079964.3721908.9649978.264 1907.589988.4451908.139
10000.091907.28210011.151907.05610021.961911.35710032.781920.96610036.781925.021
10043.311930.78210053.691935.44710063.991938.57310074.061939.11410076.911938.921
#Mann= 3 , 0 , 0
9755.294  0.0437       09755.294  0.0437       010076.91  0.0437       0
#XS Ineff= 2 , 0
       0                               0
Bank Sta=9755.294,10076.91
Exp/Cntr=0.3,0.1

Type RM Length L Ch R = 1 ,3912.558,491.864900,491.864900,491.864900
XS GIS Cut Line= 6
710055.275973141770487.325642958710173.627554357 770794.28921321
710238.421536237771031.878415599710361.456209809771161.950503096
710402.915220588771234.251896709710458.992406666771507.490062907
#Sta/Elev= 30
9307.8681952.8329444.7031945.8379605.4661936.0059637.589 1935.039709.6841924.884
9730.2831924.3939792.0781926.2459843.8571926.6269854.3681924.9339874.7761918.621
9887.0991916.6269896.1341916.2899914.7911919.2769957.6021916.513 9966.891911.641
9970.9851908.4089981.9371905.03510011.271903.75310039.481910.50410054.071912.686
10079.291914.414 10114.81914.94110136.881916.27210153.761922.43810179.481925.474
10200.181937.88310302.071941.69810332.521943.72910403.571945.131 10426.41944.218
#Mann= 3 , 0 , 0
9307.868  0.0815       09307.868  0.0815       0 10426.4  0.0815       0
#XS Ineff= 2 , 0
       0                               0
Bank Sta=9307.868,10426.4
Exp/Cntr=0.3,0.1

Type RM Length L Ch R = 1 ,3420.693,860.351400,860.351400,860.351400
XS GIS Cut Line= 6
709884.773812469  770475.8596725709925.923110413 770776.33042038
709932.117130398770883.889664702709933.006211963771046.508642585
709959.789862067771342.360365197709909.876667589771685.242309645
#Sta/Elev= 30
9499.0511952.7449660.1141950.6639700.4241944.9659740.6771944.3259770.866 1939.51
9811.078  1937.69921.2431940.3579931.2431937.7029941.2441932.7149951.2451930.745
9961.2461925.2869981.2471910.1649991.2481904.90910001.251903.83810021.261907.029
10031.261911.25410051.271915.626 10121.61918.04210211.931918.35410252.071917.161
10302.251918.924 10342.41917.39410362.471918.08710382.631916.02810423.05 1906.76
10453.371914.71310493.79 1928.5110574.641948.16910645.371951.84810716.361951.982
#Mann= 3 , 0 , 0
9499.051  0.0589       09499.051  0.0589       010716.36  0.0589       0
#XS Ineff= 2 , 0
       0                               0
Bank Sta=9499.051,10716.36
Exp/Cntr=0.3,0.1

Type RM Length L Ch R = 1 ,2560.342,615.243300,615.243300,615.243300
XS GIS Cut Line= 4
709801.369723141770595.832587406709764.477362037770917.013142973
709650.030372143771255.000000015 709308.74819535771657.030504063
#Sta/Elev= 30
  9136.61950.9479196.1561947.7939347.1431943.5789387.4061938.6849397.4711935.798
9427.6691936.382  9447.81938.7929468.325 1935.359616.1331923.3529732.2681922.994
9795.6151919.416 9816.731922.1579855.4071916.9479908.5511916.7939921.6681915.073
9934.7851910.8759974.1371910.3899994.4771904.69310025.38 1903.7310040.831908.058
10052.841913.45710056.291915.65910071.741931.11910087.191943.16410092.191946.686
10105.311952.43210133.551955.78310275.831965.13810318.971970.12210344.081975.271
#Mann= 3 , 0 , 0
  9136.6  0.0586       0  9136.6  0.0586       010344.08  0.0586       0
#XS Ineff= 2 , 0
       0                               0
Bank Sta=9136.6,10344.08
Exp/Cntr=0.3,0.1

Type RM Length L Ch R = 1 ,1945.099,245.932400,245.932400,245.932400
XS GIS Cut Line= 6
709537.524030419770413.167834637709500.681662014770634.506125611
709426.890607975770797.625053331709379.399912908770857.465472184
709084.684445101 771102.63079474709022.871669083771221.959218934
#Sta/Elev= 30
9499.1371993.3399511.0171992.4769571.267 1993.449591.4881990.5289627.5811977.867
9652.3951972.3499665.5861970.7289703.7861970.3759735.0181963.0329745.5441958.719
9766.6651954.2349820.8071950.1969867.6261949.8029877.3641948.267 9900.521937.713
9949.5841925.4619963.1731918.9359976.762  1906.99985.6311904.29910009.521903.315
10026.451904.67610042.081910.34410048.951911.53310072.251912.67610115.731918.236
10196.721938.23710282.281947.04510335.831954.36910441.131955.56510500.921967.402
#Mann= 3 , 0 , 0
9499.137    0.04       09499.137    0.04       010500.92    0.04       0
#XS Ineff= 2 , 0
       0                               0
Bank Sta=9499.137,10500.92
Exp/Cntr=0.3,0.1

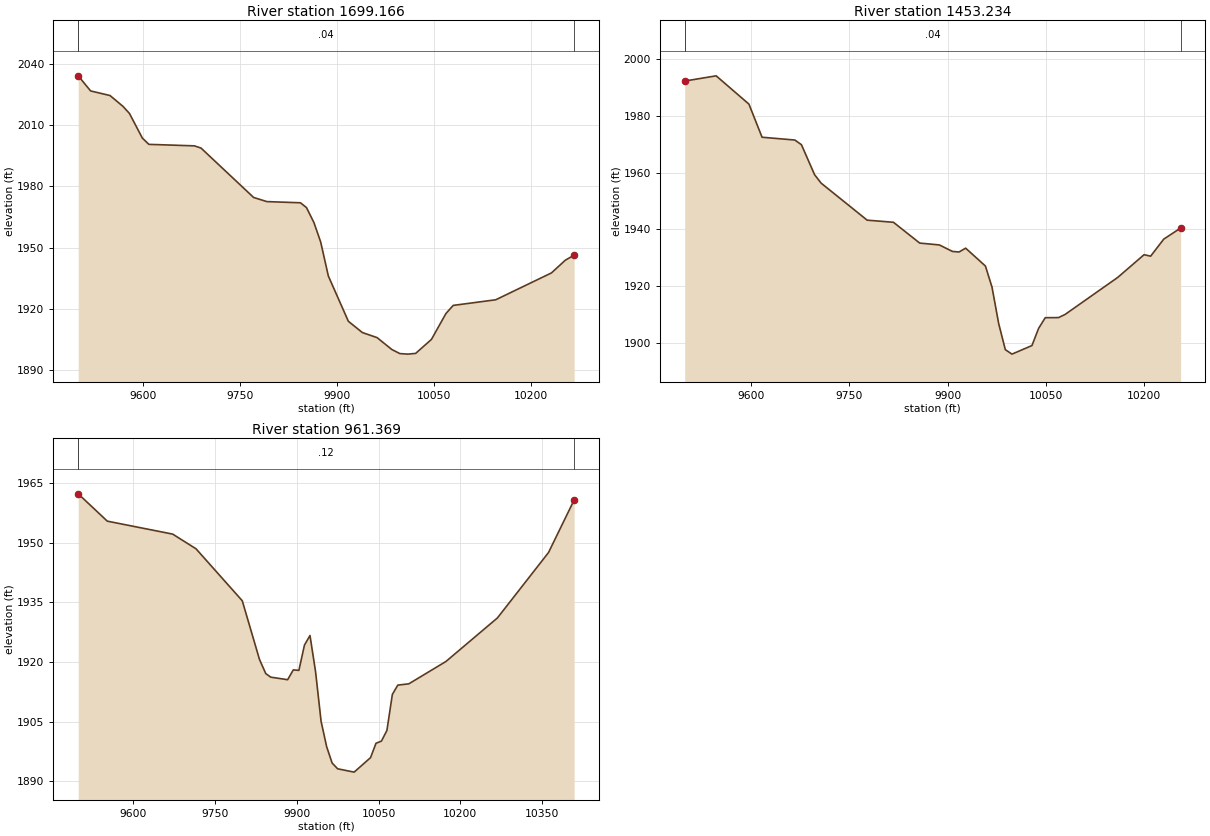
Type RM Length L Ch R = 1 ,1699.166,245.932500,245.932500,245.932500
XS GIS Cut Line= 6
709266.892609021770265.868737816709253.306785508770439.603806563
709204.448118814770648.097450659709182.062851438770702.665154877
709100.469153073770838.900312533709041.255620718770987.746996627
#Sta/Elev= 30
 9499.122034.0699518.2762026.6869548.3162024.4289568.3422019.1419578.355 2015.68
9598.3972003.5879608.4592000.5429678.939 1999.819689.0891998.7299770.4521974.564
 9791.011972.5399842.8021971.9679852.1671969.6379863.7351962.2849874.2021952.752
9886.0411936.1369916.9881913.9989938.6061908.4869961.4241906.0049984.1891900.198
9996.5381898.19410008.851897.92410021.061898.27410045.471905.11310067.951917.802
10079.191921.75810144.941924.51110231.151937.65510252.661943.89210266.241946.337
#Mann= 3 , 0 , 0
 9499.12    0.04       0 9499.12    0.04       010266.24    0.04       0
#XS Ineff= 2 , 0
       0                               0
Bank Sta=9499.12,10266.24
Exp/Cntr=0.3,0.1

Type RM Length L Ch R = 1 ,1453.234,491.864900,491.864900,491.864900
XS GIS Cut Line= 6
708926.388901416770237.011173307708925.753795762770361.640782816
708911.717036527770621.866561214708918.787132742770708.513624384
708939.797563684 770841.61505911708948.592599436770990.651083851
#Sta/Elev= 30
9499.0441992.2219547.0391994.0659597.0481984.1139617.0521972.4569667.1361971.464
9677.1551969.8129697.1931959.2569707.2121956.2869777.3461943.2699817.423 1942.52
9857.4721935.2049887.4771934.5439907.4971932.2599917.5071932.0629927.5381933.408
9957.7261927.1259967.7891919.6719977.9041906.9059988.0481897.6919998.1911896.117
10028.671899.13810038.83 1905.1810048.981908.93910069.161908.97410079.251910.089
10159.581923.12810199.65 1931.1110209.671930.591 10229.71936.593 10255.41940.494
#Mann= 3 , 0 , 0
9499.044    0.04       09499.044    0.04       0 10255.4    0.04       0
#XS Ineff= 2 , 0
       0                               0
Bank Sta=9499.044,10255.4
Exp/Cntr=0.3,0.1

Type RM Length L Ch R = 1 , 961.369,0.000000,0.000000,0.000000
XS GIS Cut Line= 6
708348.474864577770076.480978305708473.917086069770391.868919042
708498.439878691770500.268648383708518.727488661770676.435641473
708561.108508185770741.381620678708699.445341463770889.837787085
#Sta/Elev= 30
9499.0421962.3539552.3971955.474 9672.33 1952.219715.1621948.5139800.0431935.419
9831.5631920.6629843.1271917.0859852.3391916.1859883.2651915.5479893.6411918.016
9903.8971917.8959914.0761924.2589924.2551926.6719934.4341917.6099944.6131905.067
9954.755 1898.719964.8571894.5689974.9591893.11310005.261892.27210035.341895.922
10045.341899.53610055.341900.08910065.351902.76410075.351911.83910085.351914.184
10105.551914.50510173.581920.12710268.081931.09710361.881947.57910408.861960.805
#Mann= 3 , 0 , 0
9499.042    0.12       09499.042    0.12       010408.86    0.12       0
#XS Ineff= 2 , 0
       0                               0
Bank Sta=9499.042,10408.86
Exp/Cntr=0.3,0.1